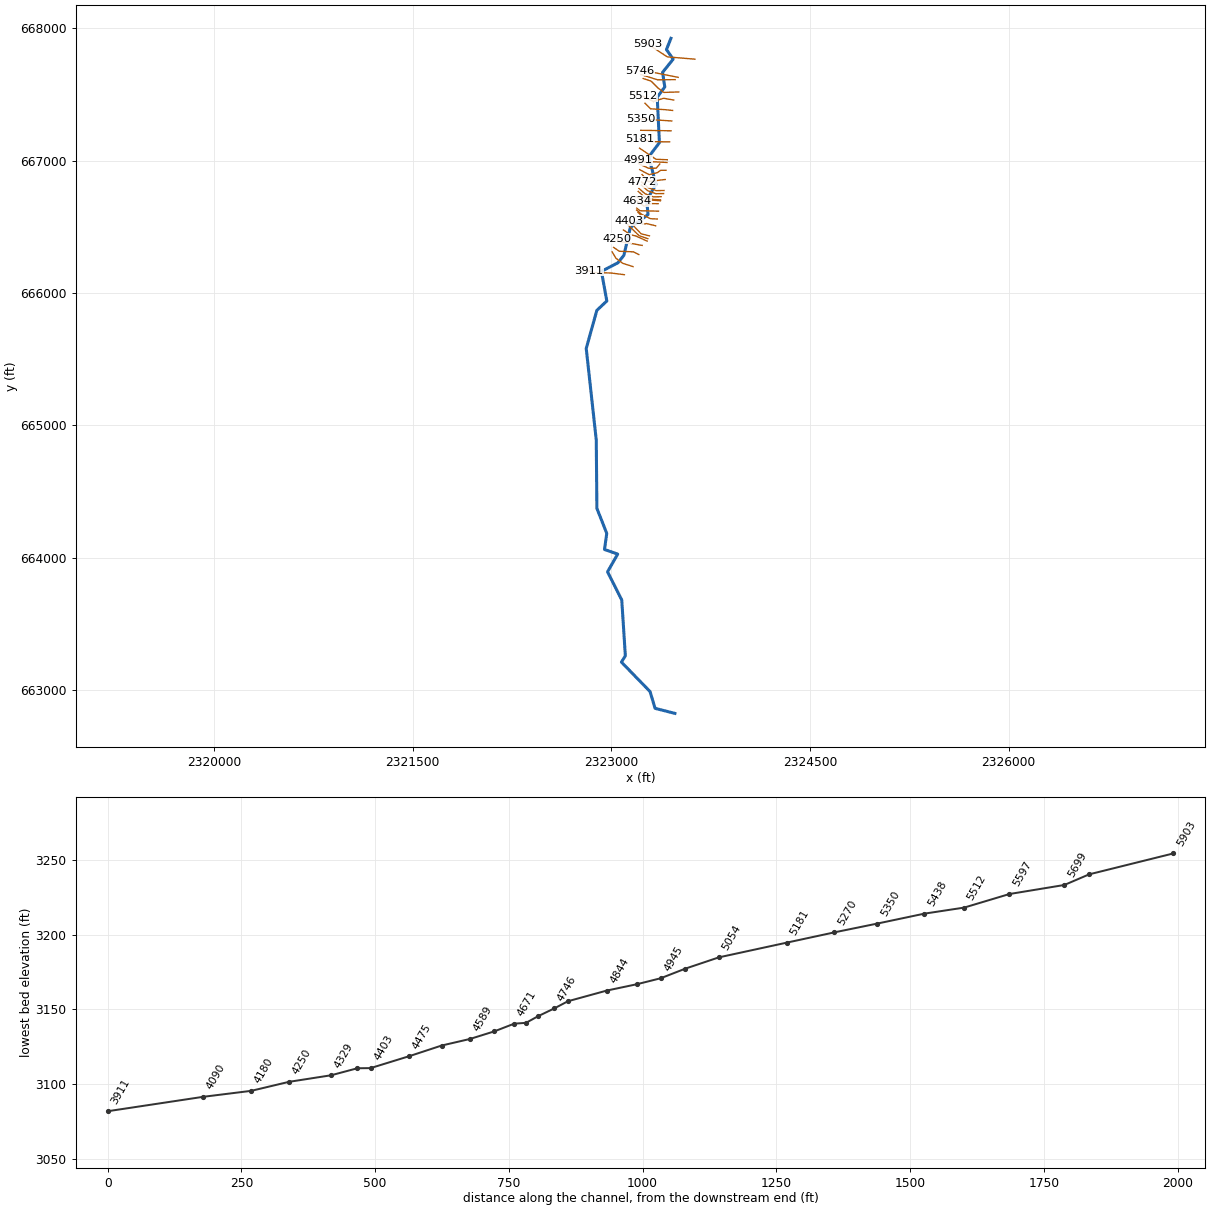
--- FSHHWKCKT1.prj (project) ---

Proj Title=FSHHWKCKT1
Current Plan=p01
Default Exp/Contr=0,0
English Units
Geom File=g01
Flow File=f01
Plan File=p01
BEGIN DESCRIPTION:
----------MODEL BY WOOD PLC 2022----------
AFH study
Randolph County, WV
HEC-RAS Version: RAS 6.2
Vertical Datum: NAVD88
Projection: NAD 1983 StatePlane West Virginia S FIPS 4702 (US Feet)
Terrain: 1-meter LIDAR (FEMA Region III 3DEP collected 2016-2018)
Land Use: 2019 NLCD
Hydrologic Method:
WV SIR2010-5033 regression equations
Additional Model Notes:
None
END DESCRIPTION:
DSS Export Rating Curves= 0
DSS Export Rating Curve Sorted= 0
DSS Export Volume Flow Curves= 0
DXF OffsetX= 0
DXF OffsetY= 0
DXF ScaleX= 0
DXF ScaleY= 0

--- FSHHWKCKT1.p01 (plan) ---

Plan Title=Floodplain
Program Version=6.20
Short Identifier=Floodplain
Geom File=g01
Flow File=f01
Subcritical Flow
K Sum by GR= 0
Std Step Tol= 0.01
Critical Tol= 0.01
Num of Std Step Trials= 20
Max Error Tol= 0.3
Flow Tol Ratio= 0.001
Split Flow NTrial= 30
Split Flow Tol= 0.02
Split Flow Ratio= 0.02
Log Output Level= 0
Friction Slope Method= 1
Unsteady Friction Slope Method= 2
Unsteady Bridges Friction Slope Method= 1
Parabolic Critical Depth
Global Vel Dist= 0 , 0 , 0
Global Log Level= 0
CheckData=True
Encroach Param=-1 ,0,0, 0
Mapping Interval=1HOUR
Computation Time Step Use Courant=        0
Computation Time Step Use Time Series=    0
Computation Time Step Count To Double=0
Computation Time Step Max Doubling=0
Computation Time Step Max Halving=0
Computation Time Step Residence Courant=0
Run HTab= 0
Run UNet= 0
Run Sediment= 0
Run PostProcess= 0
Run WQNet= 0
Run RASMapper=-1
UNET Theta= 0
UNET Theta Warmup= 0
UNET ZTol= 0
UNET ZSATol= 0
UNET MxIter= 0
UNET Max Iter WO Improvement= 0
UNET MaxInSteps= 0
UNET DtIC= 0
UNET DtMin= 0
UNET MaxCRTS= 0
UNET WFStab= 0
UNET SFStab= 0
UNET WFX= 1
UNET SFX= 1
UNET Gravity=32.174
UNET 1D Methodology=Finite Difference
UNET DSS MLevel= 1
UNET Pardiso=0
UNET DZMax Abort= 0
UNET Use Existing IB Tables= 0
UNET Froude Reduction=False
UNET Froude Limit= 0
UNET Froude Power= 0
UNET D1 Cores= 0
UNET WindReference=Eulerian
UNET WindDragFormulation=Hsu (1988)
UNET D2 Coriolis=0
UNET D2 Cores= 0
UNET D2 Theta= 1
UNET D2 Theta Warmup= 1
UNET D2 Z Tol= 0.01
UNET D2 Volume Tol= 0.01
UNET D2 Max Iterations= 20
UNET D2 Equation= 0
UNET D2 RampUpFraction=0.1
UNET D2 TimeSlices= 1
UNET D2 Turbulence Formulation=Non-Conservative (original)
UNET D2 Eddy Viscosity=0.3
UNET D2 Transverse Eddy Viscosity=0.1
UNET D2 Smagorinsky Mixing=0
UNET D2 BCVolumeCheck=0
UNET D2 Cores=0
UNET D2 SolverType=PARDISO (Direct)
UNET D2 Minimum Iterations= 2147483647
UNET D2 Maximum Iterations= 2147483647
UNET D2 Restart Number= 10
UNET D2 Relaxation Coeff=1.3
UNET D2 SOR Precondition Iterations= 10
UNET D2 ILUT Maximum Fill= 8
UNET D2 ILUT Tolerance=1E-08
UNET D1D2 MaxIter= 0
UNET D1D2 ZTol=0.01
UNET D1D2 QTol=0.1
UNET D1D2 MinQTol=1
Write IC File= 0
Write IC File at Fixed DateTime=0
Write IC File at Sim End=0
Echo Input=False
Echo Parameters=False
Echo Output=False
Write Detailed= 0
HDF Write Warmup=0
HDF Write Time Slices=0
HDF Flush=0
HDF Compression= 1
HDF Chunk Size= 1
HDF Spatial Parts= 1
HDF Use Max Rows=0
HDF Fixed Rows= 1
Calibration Method= 0
Calibration Iterations= 20
Calibration Max Change=0.05
Calibration Tolerance=0.2
Calibration Maximum=1.5
Calibration Minimum=0.5
Calibration Optimization Method= 1
WQ AD Non Conservative
WQ ULTIMATE=-1
WQ Max Comp Step=1HOUR
WQ Output Interval=15MIN
WQ Output Selected Increments= 0
WQ Output face flow=0
WQ Output face velocity=0
WQ Output face area=0
WQ Output face dispersion=0
WQ Output cell volume=0
WQ Output cell surface area=0
WQ Output cell continuity=0
WQ Output cumulative cell continuity=0
WQ Output face conc=0
WQ Output face dconc_dx=0
WQ Output face courant=0
WQ Output face peclet=0
WQ Output face adv mass=0
WQ Output face disp mass=0
WQ Output cell mass=0
WQ Output cell source sink temp=0
WQ Output nsm pathways=0
WQ Output nsm derived pathways=0
WQ Create Restart=0
WQ Fixed Restart=0
WQ System Summary=0
WQ Write To DSS=0
Sorting and Armoring Iterations= 10
XS Update Threshold= 0.02
Bed Roughness Predictor= 0
Hydraulics Update Threshold= 0.02
Energy Slope Method= 1
Volume Change Method= 1
Sediment Retention Method= 0
Sediment TS Multiplier= 1
Warm Up Method= 0
XS Weighting Method= 0
Number of US Weighted Cross Sections= 1
Number of DS Weighted Cross Sections= 1
Upstream XS Weight=0
Main XS Weight=1
Downstream XS Weight=0
Number of DS XS's Weighted with US Boundary= 1
Upstream Boundary Weight= 1
Weight of XSs Associated with US Boundary= 0
Number of US XS's Weighted with DS Boundary= 1
Downstream Boundary Weight= 0.5
Weight of XSs Associated with DS Boundary= 0.5
Percentile Method= 0
Sediment Output Level= 3
Mass or Volume Output= 0
Output Increment Type= 1
Profile and TS Output Increment= 1
Transport Output Increment 1
XS Output Flag= 0
XS Output Increment= 10
Read HDF5 Sediment Hotstart= 0
Sediment Hotstart Type= 0
Write Gradation File= 0
Read Gradation Hotstart= 0
Write HDF5 File= 1
Write Binary Output= 1
Write DSS Sediment File= 0
DSS Sediment Output Type= 1
SV Curve= 0
Specific Gage Flag= 0
Subcell Erosion Methods= 0
Subcell Deposition Methods= 0
Advection Scheme= 1
Matrix Solver= 0
Implicit Weighting Factor= 1
Maximum Outer Loop Convergence Iterations= 5
Convergence Maximum Absolute= 0.001
Convergence RMSE= 0.0001
Grain Fractions Max Abs Error= 0.001
Max Subgrid Regions= 1
Max Subgrid Length Scale= 3.402823E+38
Initial Layer Thickness= 3.402823E+38
Min Layer Thickness= 3.402823E+38
Max Layer Thickness= 3.402823E+38
Number of Layers= 5

--- FSHHWKCKT1.f01 (steady flow) ---

Flow Title=Flow
Program Version=6.20
Number of Profiles= 1
Profile Names=P100yr
River Rch & RM=FSHHWKCKT1,Main,5903
     368
River Rch & RM=FSHHWKCKT1,Main,3267
     416
River Rch & RM=FSHHWKCKT1,Main,2626
     463
Boundary for River Rch & Prof#=FSHHWKCKT1,Main            , 1
Up Type= 0
Dn Type= 3
Dn Slope=0.04479
DSS Import GetInterval= 0
DSS Import GetPeak= 0
DSS Import FillOption= 0

--- FSHHWKCKT1.g01 (geometry) ---

Geom Title=Geometry
Program Version=6.20

River Reach=FSHHWKCKT1      ,Main
Reach XY= 30
      2323449.36667923.5750000032323415.68000001      667838.853
2323466.37400001667766.2830000222323386.16599999667666.630999997
2323403.18000002667556.5610000042323345.88800003667479.478000015
2323362.56400869667135.7969538922323282.42165813667029.557275852
     2323335.848666820.0380000032323265.99398374666701.003787994
2323276.85295495666592.6925110642323142.61800003666493.996000022
2323094.27279542666285.0597319692323048.78757352666228.433213271
2322924.67309167666163.6329303152322965.22886076665940.142805831
2322889.90101279665868.8745424822322809.83698276665581.546164294
2322885.61589569664889.6125188642322890.35207775664373.819739496
 2322964.7777958664185.0490546122322947.82215554664063.200077773
2323047.30816924664028.4904547252322971.04699999663894.691000015
2323078.12385932 663681.750803022323105.29255915 663260.06250461
2323075.69818726663212.5635377292323291.73710204662990.457776707
2323329.75648408 662863.563584542323479.55792032662825.569251781

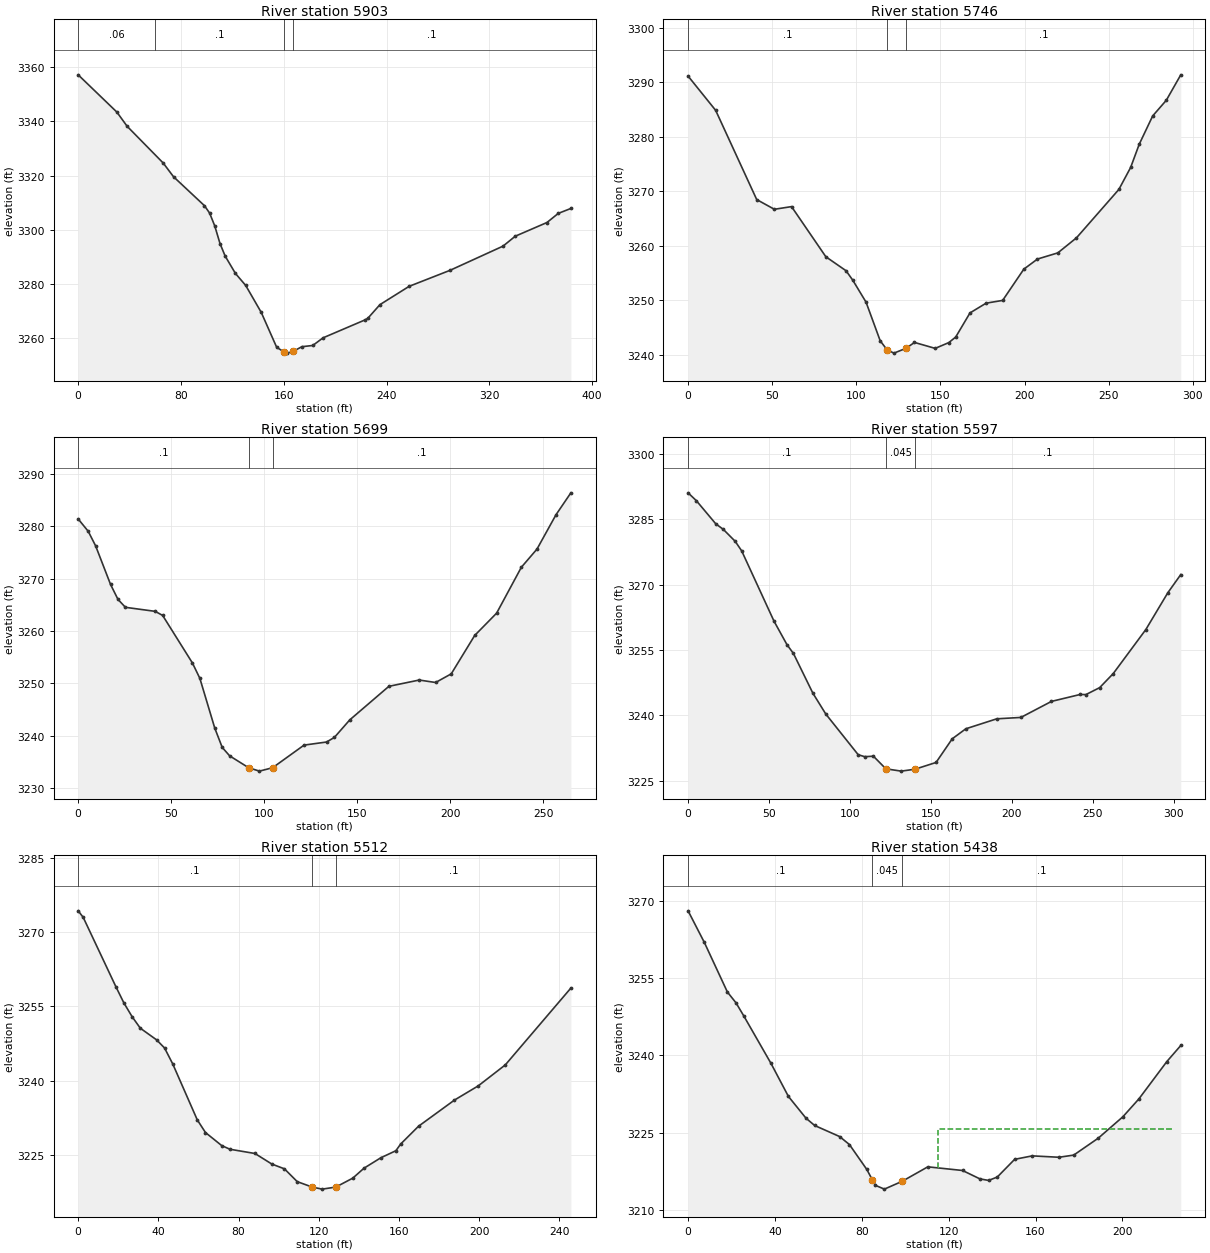
Type RM Length L Ch R = 1 ,5903    ,156.5,157.6,157.4
XS GIS Cut Line= 3
2323630.14555453667766.1992555022323421.72823947667783.645953821
2323276.02473189667879.367028383
#Sta/Elev= 30
       0 3357.21    30.1 3343.45    38.1  3338.2    66.2 3324.61    74.2 3319.56
    98.3 3308.85   102.3 3306.13   106.3 3301.39   110.4 3294.86   114.4 3290.24
   122.4 3283.82   130.4 3279.38   142.5 3269.42   154.5 3256.53   160.1 3254.84
   162.5 3254.37   167.6 3255.09   174.1 3256.74   182.6  3257.2   190.6 3260.02
   223.2 3266.63   225.4 3267.21   234.9 3272.29   257.6 3279.05   289.4 3284.96
   330.7 3293.91   340.2 3297.57   364.9 3302.64   373.7 3306.01   383.5 3307.83
#Mann= 4 ,-1,0
       0     .06       0      60      .1       0   160.1    .045       0
   167.6      .1       0
Bank Sta=160.1,167.6
XS Rating Curve= 0 ,0
Exp/Cntr(USF)=0,0
Exp/Cntr=0.3,0.1

Type RM Length L Ch R = 1 ,5746    ,44.2,46.3,46.6
XS GIS Cut Line= 3
 2323504.2464072667628.9833308842323330.25095639667663.405195135
2323215.66858635667678.022699132
#Sta/Elev= 30
       0 3291.11    16.4 3284.83    40.8 3268.48    51.3  3266.7    61.5 3267.19
    81.9    3258    93.9 3255.44    97.9 3253.71   105.8 3249.68   114.2 3242.61
   118.3 3240.94   122.4 3240.34   129.6 3241.23   134.6  3242.3   146.9 3241.21
     155 3242.27   159.1 3243.29   167.6 3247.71   177.2  3249.5     187    3250
   199.6 3255.73   207.7 3257.58   219.8 3258.71   230.9 3261.47   256.1 3270.34
   263.1 3274.37   268.2 3278.62   276.2 3283.81   284.3 3286.68   292.9 3291.34
#Mann= 3 ,-1,0
       0      .1       0   118.3    .045       0   129.6      .1       0
Bank Sta=118.3,129.6
XS Rating Curve= 0 ,0
Exp/Cntr(USF)=0,0
Exp/Cntr=0.3,0.1

Type RM Length L Ch R = 1 ,5699    ,106,102.7,94.8
XS GIS Cut Line= 3
2323481.61285262667611.5366325652323348.64071949 667610.59356779
2323222.74157216667649.730755912
#Sta/Elev= 30
       0  3281.4     5.4 3279.04     9.4 3276.24    17.4 3268.89    21.4 3266.03
    25.4 3264.52    41.4 3263.75    45.4 3262.97    61.4 3253.89    65.4 3250.95
    73.4 3241.46    77.4 3237.77    81.4 3236.15    91.63233.882    97.4 3233.23
   104.53233.879   121.4  3238.2   133.5 3238.79   137.7 3239.67     146 3243.03
     167 3249.43   183.3 3250.63   192.1 3250.16   200.5 3251.81   213.1 3259.14
   224.9 3263.41   238.2 3272.18   246.6 3275.65   256.8  3282.2   264.8 3286.39
#Mann= 3 ,-1,0
       0      .1       0    91.6    .045       0   104.5      .1       0
Bank Sta=91.6,104.5
XS Rating Curve= 0 ,0
Exp/Cntr(USF)=0,0
Exp/Cntr=0.3,0.1

Type RM Length L Ch R = 1 ,5597    ,79.7,84.6,91.4
XS GIS Cut Line= 5
2323509.25665562667518.5387348852323396.37180217667515.143701699
 2323351.8119916667548.6696544152323299.61335636667600.443910508
2323240.62465474 667619.96535133
#Sta/Elev= 30
       0 3291.12     5.1 3289.32    17.1    3284    21.8 3282.71    29.1 3279.98
    33.1 3277.79    53.1 3261.62    61.1 3256.23    65.1  3254.2    77.1 3245.08
    85.1 3240.28   105.1 3230.94   109.1 3230.49   114.5  3230.6   122.23227.698
   131.7 3227.17   140.2 3227.61   153.2 3229.16   163.2  3234.6   171.6  3236.9
   190.7 3239.19   205.6 3239.51   224.5 3243.19   242.2 3244.78   245.8 3244.76
   254.3 3246.36   262.7  3249.6   282.8  3259.7   296.4 3268.16   304.4 3272.34
#Mann= 3 ,-1,0
       0      .1       0   122.2    .045       0   140.2      .1       0
Bank Sta=122.2,140.2
XS Rating Curve= 0 ,0
Exp/Cntr(USF)=0,0
Exp/Cntr=0.3,0.1

Type RM Length L Ch R = 1 ,5512    ,75.7,74.5,72.2
XS GIS Cut Line= 4
2323470.63815312667457.4281375292323395.09866472667471.008270275
2323317.01290144667446.8186588222323238.92713815667485.861540466
#Sta/Elev= 30
       0 3274.32     2.5 3273.01    18.8    3259    22.8 3255.71    26.9 3252.93
      31  3250.6    39.1 3248.25    43.1  3246.6    47.2 3243.36    59.4 3232.09
    63.5 3229.52    71.6 3226.88    75.7 3226.14    88.2 3225.28    96.6 3223.15
   102.9 3222.18   109.3 3219.59   116.73218.503   121.7 3218.08   128.5 3218.49
     137  3220.3   142.6 3222.31     151 3224.42   158.5 3225.84   160.9  3227.2
   169.8 3230.79   187.7 3236.07   199.6 3238.95   213.1 3243.19   245.8 3258.71
#Mann= 3 ,-1,0
       0      .1       0   116.7    .045       0   128.5      .1       0
Bank Sta=116.7,128.5
XS Rating Curve= 0 ,0
Exp/Cntr(USF)=0,0
Exp/Cntr=0.3,0.1

Type RM Length L Ch R = 1 ,5438    ,85.9,87.6,86.4
XS GIS Cut Line= 4
2323462.15057016667378.9179950932323404.12515082667385.050118059
 2323295.7516238667391.2647396262323253.35602919667433.662905224
#Sta/Elev= 30
       0 3268.08     7.5 3261.93    18.1 3252.31    22.1 3250.19    25.7 3247.63
    38.2 3238.43    46.2 3232.03    54.3  3227.8    58.3 3226.38    69.8 3224.23
    74.3 3222.68    82.3 3217.85    84.9 3215.79    86.3 3214.75    90.4 3214.02
   98.59 3215.54   110.4 3218.35   126.4 3217.64   134.4 3216.01   138.4 3215.71
   142.4 3216.37   150.4 3219.81   158.5 3220.48   170.8 3220.21   177.6 3220.63
   188.9 3223.92   200.2 3228.06   207.6 3231.54   220.5 3238.81   226.9 3241.92
#Mann= 3 ,-1,0
       0      .1       0    84.9    .045       0   98.59      .1       0
#XS Ineff= 1 ,-1
  115.18223.3969 3225.75
Permanent Ineff=
       F
Bank Sta=84.9,98.59
XS Rating Curve= 0 ,0
Exp/Cntr(USF)=0,0
Exp/Cntr=0.3,0.1

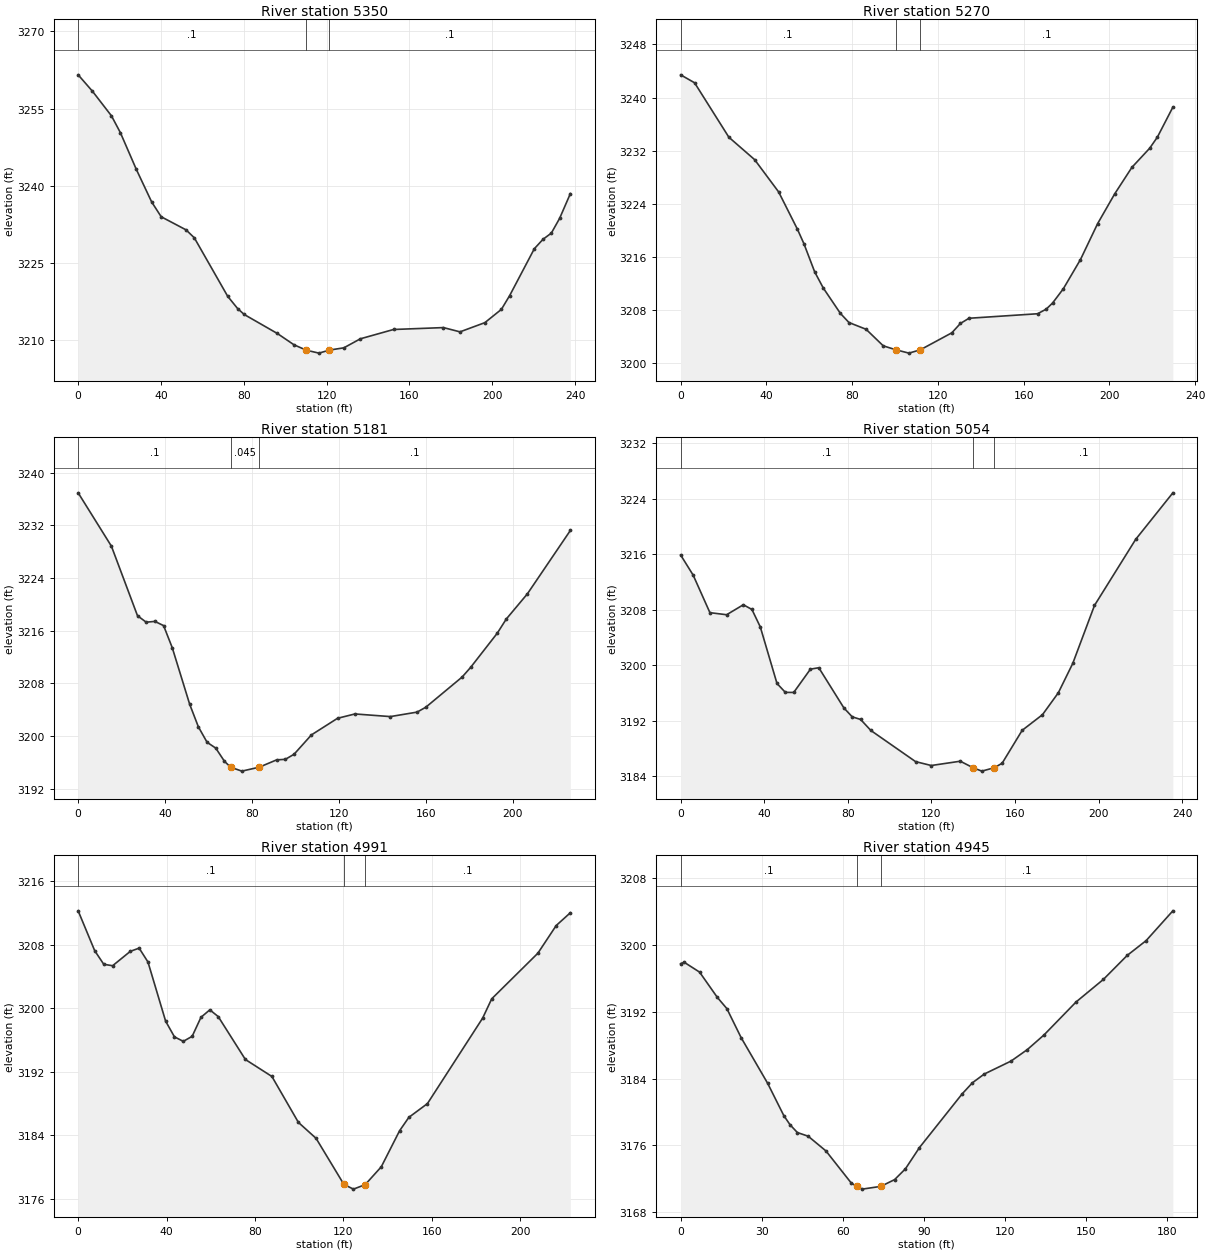
Type RM Length L Ch R = 1 ,5350    ,79.8,80.3,80.3
XS GIS Cut Line= 2
2323456.20926208 667299.559094362323218.98131818667314.412364551
#Sta/Elev= 30
       0 3261.56     6.9 3258.37    16.1 3253.57    20.4  3250.3    28.1 3243.15
    35.5 3236.82    40.1 3233.94    52.1 3231.39    56.1 3229.84    72.2 3218.47
      77 3216.08    80.2 3214.92    96.2 3211.22   104.2 3209.03  110.173207.971
   116.3  3207.4  121.323207.992   128.3 3208.43   136.3 3210.19   152.3    3212
   176.4 3212.37   184.4 3211.54   196.4 3213.33   204.4 3215.92   208.4 3218.61
   220.3 3227.72   224.5 3229.56   228.5 3230.75   232.5 3233.62   237.7 3238.45
#Mann= 3 ,-1,0
       0      .1       0  110.17    .045       0  121.32      .1       0
Bank Sta=110.17,121.32
XS Rating Curve= 0 ,0
Exp/Cntr(USF)=0,0
Exp/Cntr=0.3,0.1

Type RM Length L Ch R = 1 ,5270    ,87.4,88.3,87.1
XS GIS Cut Line= 2
2323450.69233315667225.2927434072323221.10321392667229.112155741
#Sta/Elev= 30
       0 3243.42     6.5 3242.22    22.5 3234.02    34.5 3230.65    45.7 3225.79
    54.5 3220.15    57.5 3217.99    62.5 3213.76    66.5 3211.33    74.5  3207.5
    78.5 3206.12    86.5  3205.1    94.5 3202.61   100.3 3202.02   106.5 3201.51
   111.8 3202.01   126.5 3204.57   130.5 3205.98   134.5 3206.76   166.5 3207.44
   170.5 3208.13   173.5 3209.06   178.5  3211.2   186.5  3215.6   194.5 3221.01
   202.5 3225.51   210.5 3229.49   218.8 3232.37   222.4 3234.05   229.6 3238.55
#Mann= 3 ,-1,0
       0      .1       0   100.3    .045       0   111.8      .1       0
Bank Sta=100.3,111.8
XS Rating Curve= 0 ,0
Exp/Cntr(USF)=0,0
Exp/Cntr=0.3,0.1

Type RM Length L Ch R = 1 ,5181    ,130.9,127.7,122.9
XS GIS Cut Line= 3
2323439.47205581667141.7178309092323305.79262409667143.415347502
 2323215.3998655667164.209925769
#Sta/Elev= 30
       0 3236.93    15.3 3228.83    27.3 3218.27    31.3 3217.29    35.3 3217.41
    39.3 3216.77    43.3  3213.4    51.3 3204.83    55.3  3201.4    59.3 3199.06
    63.3 3198.17    67.3 3196.17   70.153195.272    75.3 3194.68    83.3 3195.28
    91.3 3196.39    95.3 3196.47    99.3 3197.24   107.3 3200.18   119.3  3202.7
   127.3 3203.36   143.6 3202.96   155.9 3203.64   159.9 3204.38   176.6 3208.96
   180.5 3210.42   192.8 3215.63   196.9 3217.76   206.6 3221.58   226.4 3231.22
#Mann= 3 ,-1,0
       0      .1       0   70.15    .045       0    83.3      .1       0
Bank Sta=70.15,83.3
XS Rating Curve= 0 ,0
Exp/Cntr(USF)=0,0
Exp/Cntr=0.3,0.1

Type RM Length L Ch R = 1 ,5054    ,57.1,62.6,66.2
XS GIS Cut Line= 3
2323422.19545063667006.6898427442323336.22145762667010.372985544
2323212.52047077667094.203324983
#Sta/Elev= 30
       0 3215.91       6    3213      14  3207.6      22  3207.3      30 3208.74
    34.1 3208.06    38.1 3205.55    46.1 3197.39    50.1 3196.11    54.1  3196.1
    62.1 3199.46    66.1 3199.66    78.1 3193.87    82.1 3192.58    86.1 3192.21
      91 3190.62   112.4 3186.13   119.9 3185.57   133.8 3186.19   139.9 3185.25
   144.1 3184.76  149.993185.246   153.8 3185.89   163.4 3190.64   173.1 3192.89
   180.7 3196.05   187.6 3200.28     198 3208.64   217.7 3218.16   235.5 3224.87
#Mann= 3 ,-1,0
       0      .1       0   139.9    .045       0  149.99      .1       0
Bank Sta=139.9,149.99
XS Rating Curve= 0 ,0
Exp/Cntr(USF)=0,0
Exp/Cntr=0.3,0.1

Type RM Length L Ch R = 1 ,4991    ,48.3,46.3,45.6
XS GIS Cut Line= 4
2323419.71265533666985.9429037632323312.76910995666991.884211839
2323280.09191553666981.2747331312323202.00615225 667004.19120714
#Sta/Elev= 30
       0  3212.3     7.5 3207.27    11.6 3205.56    15.6 3205.38    23.6 3207.19
    27.6  3207.6    31.6 3205.85    39.6 3198.39    43.6 3196.41    47.6 3195.85
    51.6 3196.48    55.6 3198.88    59.6 3199.82    63.4 3198.97    75.7 3193.56
    87.7 3191.42    99.7 3185.63   107.7 3183.62   120.3 3177.81   124.6 3177.22
   129.93177.781   137.2 3180.03   145.5 3184.58   149.7 3186.27   158.1    3188
   183.1 3198.78   187.2 3201.21   208.1 3206.96   216.4 3210.45   222.8 3212.06
#Mann= 3 ,-1,0
       0      .1       0   120.3    .045       0   129.9      .1       0
Bank Sta=120.3,129.9
XS Rating Curve= 0 ,0
Exp/Cntr(USF)=0,0
Exp/Cntr=0.3,0.1

Type RM Length L Ch R = 1 ,4945    ,41.7,43.6,44.4
XS GIS Cut Line= 5
2323364.95965353666974.2651386862323338.79639924666943.285086321
 2323318.2050236666942.1182628482323280.01090025666942.542641995
  2323204.895791666977.341732156
#Sta/Elev= 30
       0 3197.76     1.3 3197.93       7 3196.75    13.6 3193.71    17.1 3192.38
    22.4 3188.89    32.2 3183.43    38.2 3179.55    40.5 3178.46    43.2 3177.53
    47.2 3177.09    53.8 3175.32    63.2 3171.46   65.343171.083    67.2 3170.75
    74.1 3171.08    79.2 3171.89    83.2 3173.18    88.4 3175.73   104.2 3182.16
     108 3183.49   112.4 3184.54   122.3 3186.09   128.3 3187.46   134.5 3189.22
   146.4 3193.18   156.5 3195.88   165.3 3198.75   172.3 3200.52   182.2 3204.09
#Mann= 3 ,-1,0
       0      .1       0   65.34    .045       0    74.1      .1       0
Bank Sta=65.34,74.1
XS Rating Curve= 0 ,0
Exp/Cntr(USF)=0,0
Exp/Cntr=0.3,0.1

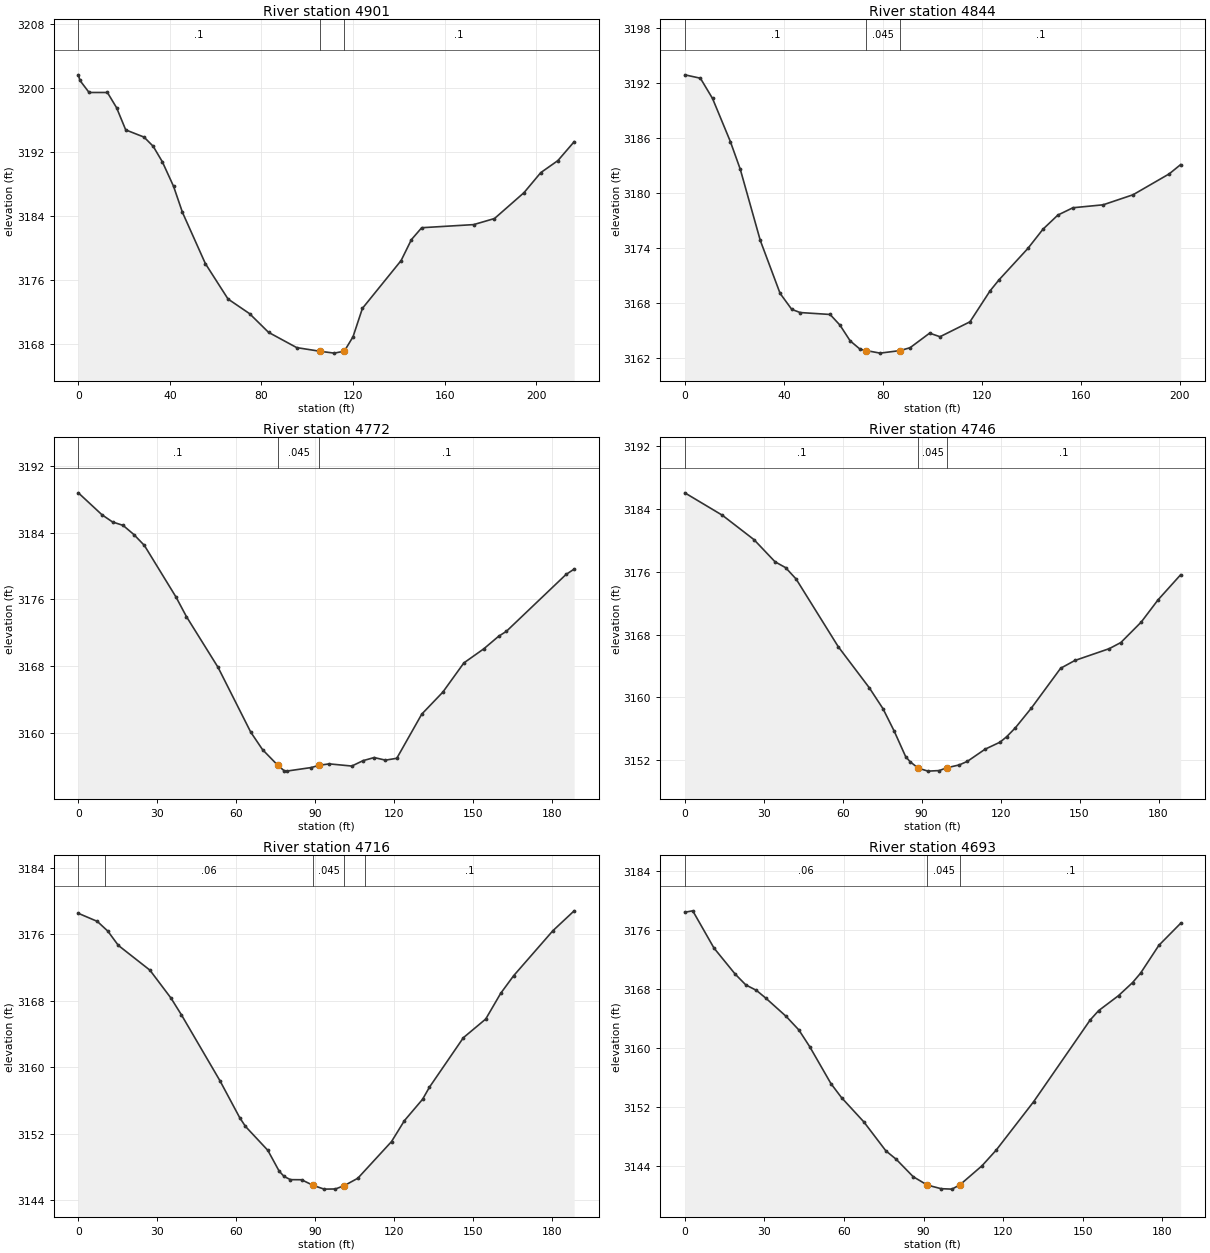
Type RM Length L Ch R = 1 ,4901    ,56.7,57.1,55.8
XS GIS Cut Line= 5
2323412.92258895666926.9542021482323371.33343242666926.954202148
2323346.71944182666908.7058987712323284.33570702666894.277007729
2323213.46438925666932.046751928
#Sta/Elev= 30
       0 3201.65      .7 3200.95     4.7 3199.44    12.7 3199.44    16.7 3197.54
    20.7 3194.76    28.7 3193.86    32.7 3192.71    36.7 3190.77    41.6  3187.7
    45.5 3184.43    55.5 3178.03    65.4  3173.6    74.8 3171.77    83.1 3169.43
    95.4 3167.52   105.6 3167.06   111.8 3166.83   116.23167.076     120 3168.88
   124.1 3172.43     141 3178.41   145.5 3181.03     150 3182.52   172.7 3182.91
   181.8 3183.67   194.7 3186.91     202 3189.41   209.5 3190.92   216.6 3193.28
#Mann= 3 ,-1,0
       0      .1       0   105.6    .045       0   116.2      .1       0
Bank Sta=105.6,116.2
XS Rating Curve= 0 ,0
Exp/Cntr(USF)=0,0
Exp/Cntr=0.3,0.1

Type RM Length L Ch R = 1 ,4844    ,75.2,72.6,67.9
XS GIS Cut Line= 5
2323406.43394046666857.6356929262323356.35720096666851.694384849
2323299.74841304666843.8698962532323278.49425573666841.305149055
2323231.58973136666894.981057976
#Sta/Elev= 30
       0 3192.89     6.3 3192.52    11.2 3190.31    18.4 3185.61    22.4 3182.59
    30.5 3174.81    38.5 3169.03    43.2 3167.29    46.6 3166.94    58.7 3166.73
    62.7 3165.56    66.8 3163.85    70.8 3162.94   73.223162.793    78.9 3162.51
86.899993162.785      91  3163.1    98.9 3164.69   103.1  3164.3   115.2 3165.93
   123.3  3169.3   126.9  3170.5   138.6 3173.94   144.7 3176.04   150.7 3177.58
   156.8 3178.38     169  3178.7   181.1  3179.8   195.7 3182.08   200.3 3183.09
#Mann= 3 ,-1,0
       0      .1       0   73.22    .045       086.89999      .1       0
Bank Sta=73.22,86.89999
XS Rating Curve= 0 ,0
Exp/Cntr(USF)=0,0
Exp/Cntr=0.3,0.1

Type RM Length L Ch R = 1 ,4772    ,24.6,25.2,23.2
XS GIS Cut Line= 4
2323397.22056047666774.6020879072323338.23185885666773.328950462
2323275.84812405666796.6698036192323228.74203859666838.258960153
#Sta/Elev= 30
       0  3188.8       9 3186.16      13  3185.3      17 3184.89    21.1 3183.79
    25.1 3182.48    37.1 3176.29    41.1 3173.92    53.1 3167.83    65.5 3160.06
      70 3157.95    75.73156.101    78.3 3155.39    79.1 3155.37    88.5  3155.8
    91.6 3156.08    95.4 3156.24   103.9 3155.98   108.2 3156.63   112.4    3157
   116.7 3156.69     121 3156.91   130.5 3162.22   138.5 3164.86   146.5 3168.37
   154.1 3170.07   159.7 3171.57   162.6 3172.15   185.3 3178.99   188.4 3179.64
#Mann= 3 ,-1,0
       0      .1       0    75.7    .045       0    91.6      .1       0
Bank Sta=75.7,91.6
XS Rating Curve= 0 ,0
Exp/Cntr(USF)=0,0
Exp/Cntr=0.3,0.1

Type RM Length L Ch R = 1 ,4746    ,30.8,30.7,31.2
XS GIS Cut Line= 4
  2323394.462096666751.4734243242323335.47339439666750.200286879
2323273.08965959666773.5411400362323225.98357413 666815.13029657
#Sta/Elev= 30
       0 3186.04    14.3 3183.18    26.3 3180.08    34.3 3177.26    38.3 3176.52
    42.3 3175.07    58.3 3166.46    70.1 3161.23    75.3 3158.57    79.6 3155.69
    83.9 3152.48    85.6 3151.82    88.7    3151    92.4 3150.62    96.7 3150.69
    99.53151.044   104.3 3151.41   107.4 3151.87   114.1 3153.41   119.8 3154.31
   122.3    3155   125.6 3156.13   131.7 3158.65   142.8 3163.71   148.2  3164.7
   161.3 3166.21   165.7 3166.99   173.4 3169.58   179.8 3172.41   188.4 3175.61
#Mann= 3 ,-1,0
       0      .1       0    88.7    .045       0    99.5      .1       0
Bank Sta=88.7,99.5
XS Rating Curve= 0 ,0
Exp/Cntr(USF)=0,0
Exp/Cntr=0.3,0.1

Type RM Length L Ch R = 1 ,4716    ,21.7,22.4,22.7
XS GIS Cut Line= 4
2323375.36503433666727.7081920192323316.37633271666726.435054574
2323253.99259791666749.7759077312323206.88651245666791.365064265
#Sta/Elev= 30
       0 3178.51     7.2 3177.54    11.2 3176.37    15.2 3174.65    27.2 3171.67
    35.2 3168.31    39.2 3166.28    53.8 3158.37    61.3 3153.93    63.5 3152.87
      72 3149.99    76.3 3147.49    78.2 3146.84    80.6 3146.46    84.8 3146.45
    89.3 3145.76    93.4 3145.32    97.7 3145.34   101.1 3145.75   106.2 3146.63
     119 3151.04   123.9 3153.56   130.8 3156.13   133.4 3157.58   146.3 3163.54
   154.8 3165.79   160.5 3168.89   165.4    3171   180.3 3176.41   188.4 3178.81
#Mann= 5 ,-1,0
       0      .1       0      10     .06       0    89.3    .045       0
   101.1     .06       0     109      .1       0
Bank Sta=89.3,101.1
XS Rating Curve= 0 ,0
Exp/Cntr(USF)=0,0
Exp/Cntr=0.3,0.1

Type RM Length L Ch R = 1 ,4693    ,20.2,22.1,22.9
XS GIS Cut Line= 4
2323371.12124285666703.5185805662323313.83005782  666707.3379929
2323249.74880643666725.5862962772323202.64272097666767.175452811
#Sta/Elev= 30
       0  3178.4       3 3178.59      11 3173.55      19 3170.02      23 3168.56
      27 3167.82    30.6 3166.75    38.2  3164.3      43 3162.46    47.1 3160.19
    55.1 3155.19    59.1 3153.29    67.5 3150.01    75.8 3146.09    79.7 3144.95
    86.1 3142.59    91.43141.462    96.6 3140.97   100.7 3140.91   103.7 3141.49
     112 3144.06   117.4  3146.2   131.5 3152.75   152.8 3163.81     156 3165.08
   163.5 3167.11   168.8 3168.88   171.8 3170.15   178.7 3173.92   186.9  3176.9
#Mann= 3 ,-1,0
       0     .06       0    91.4    .045       0   103.7      .1       0
Bank Sta=91.4,103.7
XS Rating Curve= 0 ,0
Exp/Cntr(USF)=0,0
Exp/Cntr=0.3,0.1

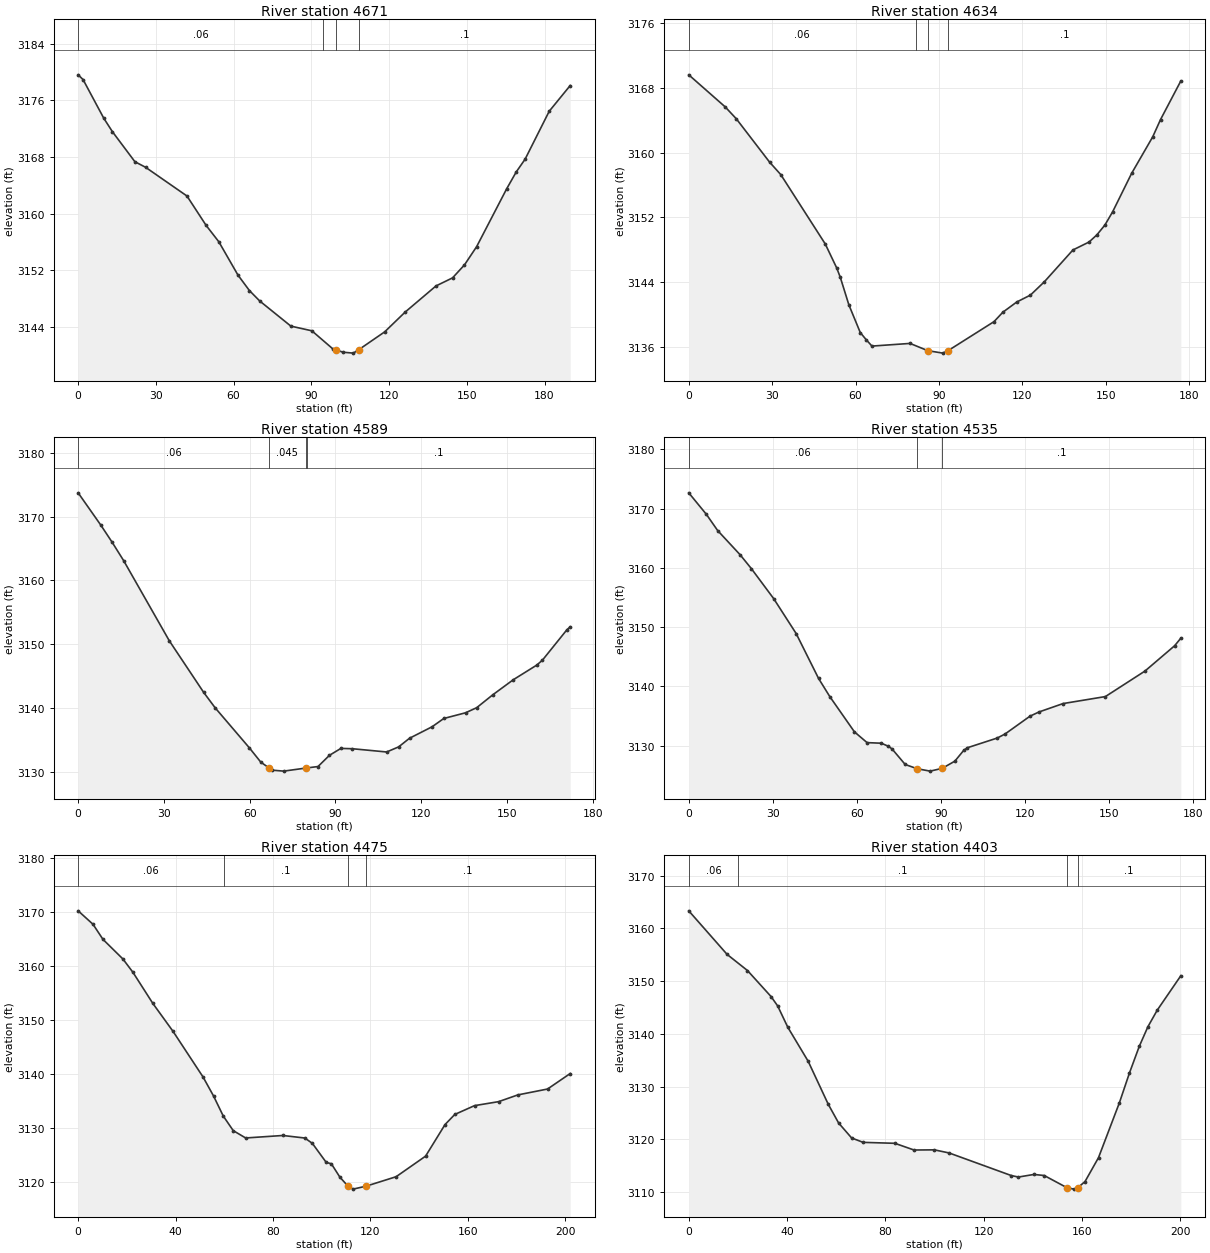
Type RM Length L Ch R = 1 ,4671    ,36.2,36.9,37.7
XS GIS Cut Line= 4
2323370.06029498666696.9407037672323295.79394402666702.457632695
2323240.62465474666696.940703767 2323189.2747778666727.920381593
#Sta/Elev= 30
       0 3179.61     1.9 3178.94     9.9 3173.48    13.2  3171.6    21.9 3167.35
      26 3166.57      42 3162.51    49.4 3158.36    54.3 3156.05    61.7 3151.34
    66.1 3149.17    70.1 3147.69    82.1 3144.15    90.2 3143.49    98.2 3140.97
    99.4 3140.82   102.2 3140.47   106.2 3140.34   108.2  3140.8   118.3 3143.34
   126.2 3146.13   138.1 3149.82   144.5 3150.96   149.1 3152.79   153.8 3155.37
   165.4 3163.54   169.1 3165.92   172.5 3167.71   181.8 3174.47   189.9  3178.1
#Mann= 4 ,-1,0
       0     .06       0   94.47      .1       0    99.4    .045       0
   108.2      .1       0
Bank Sta=99.4,108.2
XS Rating Curve= 0 ,0
Exp/Cntr(USF)=0,0
Exp/Cntr=0.3,0.1

Type RM Length L Ch R = 1 ,4634    ,48.6,45.6,43.8
XS GIS Cut Line= 4
 2323353.3058062666674.6540084152323301.74373968666675.341502635
2323246.74420206666656.0916644682323192.43215866666695.622582132
#Sta/Elev= 30
       0 3169.62    13.1 3165.66    17.1 3164.19    29.1 3158.82    33.1 3157.29
    49.1 3148.72    53.2 3145.77    54.5 3144.61    57.6 3141.19    61.7 3137.77
    63.9 3136.86    65.9  3136.1    79.6 3136.43      863135.533    91.4 3135.23
    93.3 3135.54   109.8 3139.12     113 3140.29     118 3141.55   122.9  3142.4
   127.9 3144.04   138.2 3147.98     144 3148.96   146.8 3149.84   149.7 3151.06
   152.5 3152.71   159.3 3157.44   166.9 3161.96   169.7 3164.09     177 3168.86
#Mann= 4 ,-1,0
       0     .06       0   81.57      .1       0      86    .045       0
    93.3      .1       0
Bank Sta=86,93.3
XS Rating Curve= 0 ,0
Exp/Cntr(USF)=0,0
Exp/Cntr=0.3,0.1

Type RM Length L Ch R = 1 ,4589    ,53.4,53.2,48.5
XS GIS Cut Line= 3
2323356.05578308666618.2794823542323215.80696215666621.716953455
2323191.05717022666641.654285843
#Sta/Elev= 30
       0 3173.72     7.9 3168.68    11.9 3165.97    15.9 3163.11    31.9 3150.53
    43.9 3142.46    47.9 3140.05    59.9 3133.76    63.9 3131.52   66.863130.595
    67.9 3130.27    71.9 3130.12   79.543130.595    83.9 3130.84    87.9  3132.6
    91.9 3133.68    95.9 3133.63   107.9 3133.12   112.1 3133.92   115.9 3135.27
   123.8 3137.07   127.9 3138.37   135.5 3139.26   139.4 3140.06     145 3142.07
   152.2 3144.44   160.4 3146.73   162.4 3147.51   170.9 3152.24   172.1 3152.73
#Mann= 4 ,-1,0
       0     .06       0   66.86    .045       0   79.54     .06       0
      80      .1       0
Bank Sta=66.86,79.54
XS Rating Curve= 0 ,0
Exp/Cntr(USF)=0,0
Exp/Cntr=0.3,0.1

Type RM Length L Ch R = 1 ,4535    ,62.4,60.3,57.2
XS GIS Cut Line= 4
  2323346.430864666559.1549794122323294.86879748666561.561209183
2323227.49436389666595.248425975  2323190.369676666626.529412997
#Sta/Elev= 30
       0 3172.66     6.3 3169.02    10.3  3166.3    18.3 3162.22    22.3 3159.89
    30.3  3154.8    38.3 3148.92    46.3 3141.34    50.3 3138.28    59.1 3132.32
    63.6 3130.51    68.7 3130.41    71.2 3129.89    72.5 3129.45    77.2 3126.82
    81.5  3126.1    86.1  3125.7    90.4 3126.17    94.9 3127.38    98.1 3129.22
    99.4 3129.65     110 3131.28   112.8 3131.96   121.7 3134.97   124.9 3135.68
   133.5  3137.1   148.6 3138.28   162.7 3142.58   173.3 3146.86   175.5 3148.13
#Mann= 3 ,-1,0
       0     .06       0    81.5    .045       0    90.4      .1       0
Bank Sta=81.5,90.4
XS Rating Curve= 0 ,0
Exp/Cntr(USF)=0,0
Exp/Cntr=0.3,0.1

Type RM Length L Ch R = 1 ,4475    ,71.7,72.5,72.1
XS GIS Cut Line= 6
2323334.05596803666507.9366600032323264.61905179666524.780268399
2323234.71305321666519.2803146372323222.68190435666543.342612346
 2323217.5256977666594.9046788652323201.02583641 666608.65456327
#Sta/Elev= 30
       0 3170.17     6.1 3167.68    10.2 3164.88    18.4 3161.24    22.5 3158.78
    30.7    3153      39 3147.82    51.3 3139.38    55.6 3135.87    59.6 3132.15
    63.7 3129.44    68.8 3128.08    84.1 3128.54    93.1 3128.07    96.2 3127.08
   101.9 3123.55     104  3123.3   107.5 3120.82   110.73119.219   112.9  3118.6
   118.3 3119.15   130.6  3120.9   142.7 3124.71   150.7 3130.57   154.7 3132.44
   162.8 3134.07   172.7 3134.81   180.6 3136.06   192.8 3137.15   202.1 3140.02
#Mann= 4 ,-1,0
       0     .06       0      60      .1       0   110.7    .045       0
   118.3      .1       0
Bank Sta=110.7,118.3
XS Rating Curve= 0 ,0
Exp/Cntr(USF)=0,0
Exp/Cntr=0.3,0.1

Type RM Length L Ch R = 1 ,4403    ,24.5,24.7,24.7
XS GIS Cut Line= 3
2323287.30636106666431.624801555 2323224.4006399666447.437168621
2323130.90142595666545.405095007
#Sta/Elev= 30
       0 3163.31    15.6 3155.06    23.9    3152    33.5 3147.07    36.2 3145.29
    40.3 3141.27    48.6 3134.82    56.8 3126.65      61 3123.12    66.3 3120.28
      71 3119.45    83.9 3119.27    91.7    3118     100 3118.03     106 3117.44
   131.3 3113.16   134.2 3112.88   140.5 3113.37   144.7 3113.17     154 3110.85
   156.8 3110.59   158.33110.846   161.3 3112.02   166.8 3116.56   175.3 3126.95
   179.4  3132.6   183.4 3137.65   186.9 3141.35   190.7 3144.49   200.3 3151.01
#Mann= 4 ,-1,0
       0     .06       0      20      .1       0     154    .045       0
   158.3      .1       0
Bank Sta=154,158.3
XS Rating Curve= 0 ,0
Exp/Cntr(USF)=0,0
Exp/Cntr=0.3,0.1

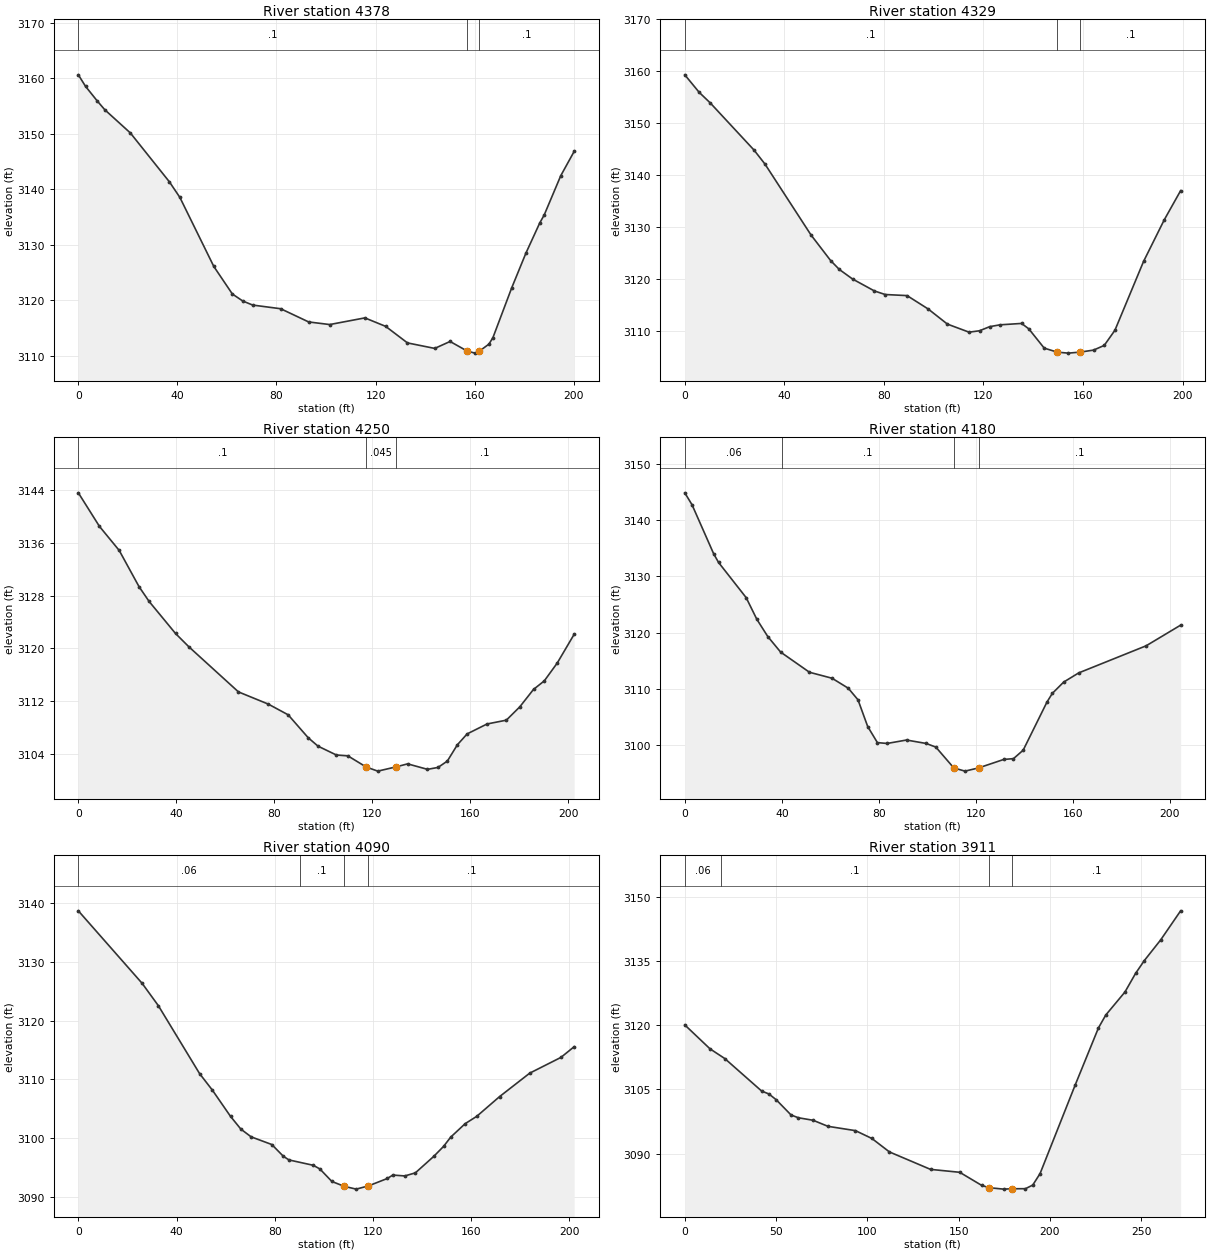
Type RM Length L Ch R = 1 ,4378    ,48.5,48.8,48.8
XS GIS Cut Line= 3
2323274.93146509666410.3124807272323209.27576706666432.999789995
2323115.43280599666524.092774179
#Sta/Elev= 30
       0 3160.64     2.9 3158.57     7.6 3155.95    10.7 3154.34      21 3150.17
    36.8 3141.34      41 3138.55    54.7 3126.11    62.2 3121.14    66.4 3119.88
    70.4 3119.15    81.7 3118.49      93 3116.11   101.5 3115.64   115.7 3116.84
   124.1 3115.31   132.9 3112.33   143.9 3111.34   150.1 3112.59   157.13110.841
   160.2 3110.49   161.93110.836   165.8 3112.12   167.4 3113.28     175 3122.27
   180.7 3128.49   186.3 3133.94   188.1 3135.38   194.8 3142.47   200.2 3146.84
#Mann= 3 ,-1,0
       0      .1       0   157.1    .045       0   161.9      .1       0
Bank Sta=157.1,161.9
XS Rating Curve= 0 ,0
Exp/Cntr(USF)=0,0
Exp/Cntr=0.3,0.1

Type RM Length L Ch R = 1 ,4329    ,75.1,78.9,79.2
XS GIS Cut Line= 4
2323269.43151133 666392.093883892323185.21346935666430.593560225
2323143.96381613666440.5622264182323090.68301406666476.311925872
#Sta/Elev= 30
       0 3159.32     5.8 3155.94    10.2 3153.93    27.8 3144.86    32.2 3142.17
    50.7 3128.53    58.6  3123.6    62.1 3121.89    67.4 3120.06    76.2 3117.76
    80.5 3117.08    89.3 3116.87    97.8 3114.29   105.5 3111.39   114.2 3109.84
   118.4 3110.11   122.5  3110.9   126.6 3111.25   135.3 3111.52   138.2 3110.48
   144.4 3106.77   149.7 3105.99   154.1 3105.81   158.9 3106.01   164.2 3106.39
   168.5 3107.29   172.8  3110.2   184.3 3123.43   192.6 3131.42   199.2 3137.05
#Mann= 3 ,-1,0
       0      .1       0   149.7    .045       0   158.9      .1       0
Bank Sta=149.7,158.9
XS Rating Curve= 0 ,0
Exp/Cntr(USF)=0,0
Exp/Cntr=0.3,0.1

Type RM Length L Ch R = 1 ,4250    ,69.5,70.6,70.7
XS GIS Cut Line= 3
2323232.65057055666359.7816555382323060.43326837666389.687654119
2323041.87092443666410.312480727
#Sta/Elev= 30
       0 3143.56     8.6 3138.49    16.7 3134.83    24.8 3129.34    28.9 3127.11
    39.7 3122.25    45.1 3120.25    65.4  3113.4    77.6 3111.55    85.7 3109.93
    93.9 3106.45    97.9 3105.18   105.4 3103.84   110.1 3103.71   117.63102.016
   122.3  3101.4   129.6 3102.03   134.5  3102.5   142.6 3101.67   146.9 3101.96
   150.7 3102.92   154.8 3105.39   158.8 3107.04   166.9 3108.54   174.8 3109.12
   180.3 3111.14   185.9 3113.78   190.3 3115.07   195.6 3117.78   202.5 3122.13
#Mann= 3 ,-1,0
       0      .1       0   117.6    .045       0   129.6      .1       0
Bank Sta=117.6,129.6
XS Rating Curve= 0 ,0
Exp/Cntr(USF)=0,0
Exp/Cntr=0.3,0.1

Type RM Length L Ch R = 1 ,4180    ,91.2,89.7,85.6
XS GIS Cut Line= 4
2323206.86953729666291.0322335132323165.61988407666311.313313011
2323059.40202704666315.4382783322323016.43363828666345.000529803
#Sta/Elev= 30
       0 3144.86       3 3142.72    11.9 3134.02    13.9 3132.49    25.3 3126.22
    29.7 3122.37    34.2 3119.31    39.5 3116.54    51.4 3112.95    60.7 3111.89
    67.4 3110.11    71.4 3108.05    75.4  3103.3    79.4 3100.44    83.4 3100.29
    91.4  3100.9    99.5 3100.29   103.5 3099.64   110.93095.937   115.5 3095.37
   121.1 3095.94   131.5 3097.45   135.5 3097.59   139.5  3099.1   149.3 3107.65
   151.5 3109.19   156.2 3111.21   162.4 3112.84   190.2 3117.66   204.4 3121.33
#Mann= 4 ,-1,0
       0     .06       0      40      .1       0   110.9    .045       0
   121.1      .1       0
Bank Sta=110.9,121.1
XS Rating Curve= 0 ,0
Exp/Cntr(USF)=0,0
Exp/Cntr=0.3,0.1

Type RM Length L Ch R = 1 ,4090    ,169.7,178.7,180.2
XS GIS Cut Line= 4
 2323163.2136543666199.5955022192323086.90179585666224.001547038
2323034.65223511666262.1574762622323005.43373075666311.313313011
#Sta/Elev= 30
       0 3138.64      26 3126.32    32.6 3122.53    49.4 3110.99    54.6 3108.19
      62 3103.73    66.2 3101.57    70.4 3100.25    78.8 3098.95    83.5 3096.96
    85.8 3096.33    95.7 3095.42    98.4  3094.8   103.3 3092.67   108.3 3091.85
   113.2 3091.37   118.2 3091.92   125.9 3093.18   128.1 3093.76     133 3093.61
   137.3 3094.13   144.8 3096.93   148.8 3098.63   151.7  3100.2   157.6 3102.49
   162.3 3103.73   171.6 3107.08   183.9 3111.07   196.6 3113.74     202 3115.56
#Mann= 4 ,-1,0
       0     .06       0   90.12      .1       0   108.3    .045       0
   118.2      .1       0
Bank Sta=108.3,118.2
XS Rating Curve= 0 ,0
Exp/Cntr(USF)=0,0
Exp/Cntr=0.3,0.1

Type RM Length L Ch R = 1 ,3911    ,40.9,42.8,41.5
XS GIS Cut Line= 4
2323097.90170338666138.4085166172322995.12131745666151.470906801
 2322857.6224734666154.564630793 2322830.4664517666168.314515198
#Sta/Elev= 30
       0 3120.04    13.8 3114.46    21.9 3112.19    42.1  3104.6    46.1 3103.92
    50.1 3102.56    58.2 3099.02    62.2 3098.37    70.3 3097.78    78.4 3096.37
    93.5 3095.36   102.5 3093.53   112.1 3090.39   134.6 3086.32   150.6 3085.64
   162.6 3082.59   166.6 3082.05   174.6 3081.71   179.5  3081.8   186.6 3081.81
   190.6 3082.66   194.6 3085.33   213.8 3105.97   226.6 3119.35   230.6 3122.35
   241.1 3127.72   246.9 3132.05   251.7 3135.05   260.7  3139.9   271.6 3146.67
#Mann= 4 ,-1,0
       0     .06       0      20      .1       0   166.6    .045       0
   179.5      .1       0
Bank Sta=166.6,179.5
XS Rating Curve= 0 ,0
Exp/Cntr(USF)=0,0
Exp/Cntr=0.3,0.1