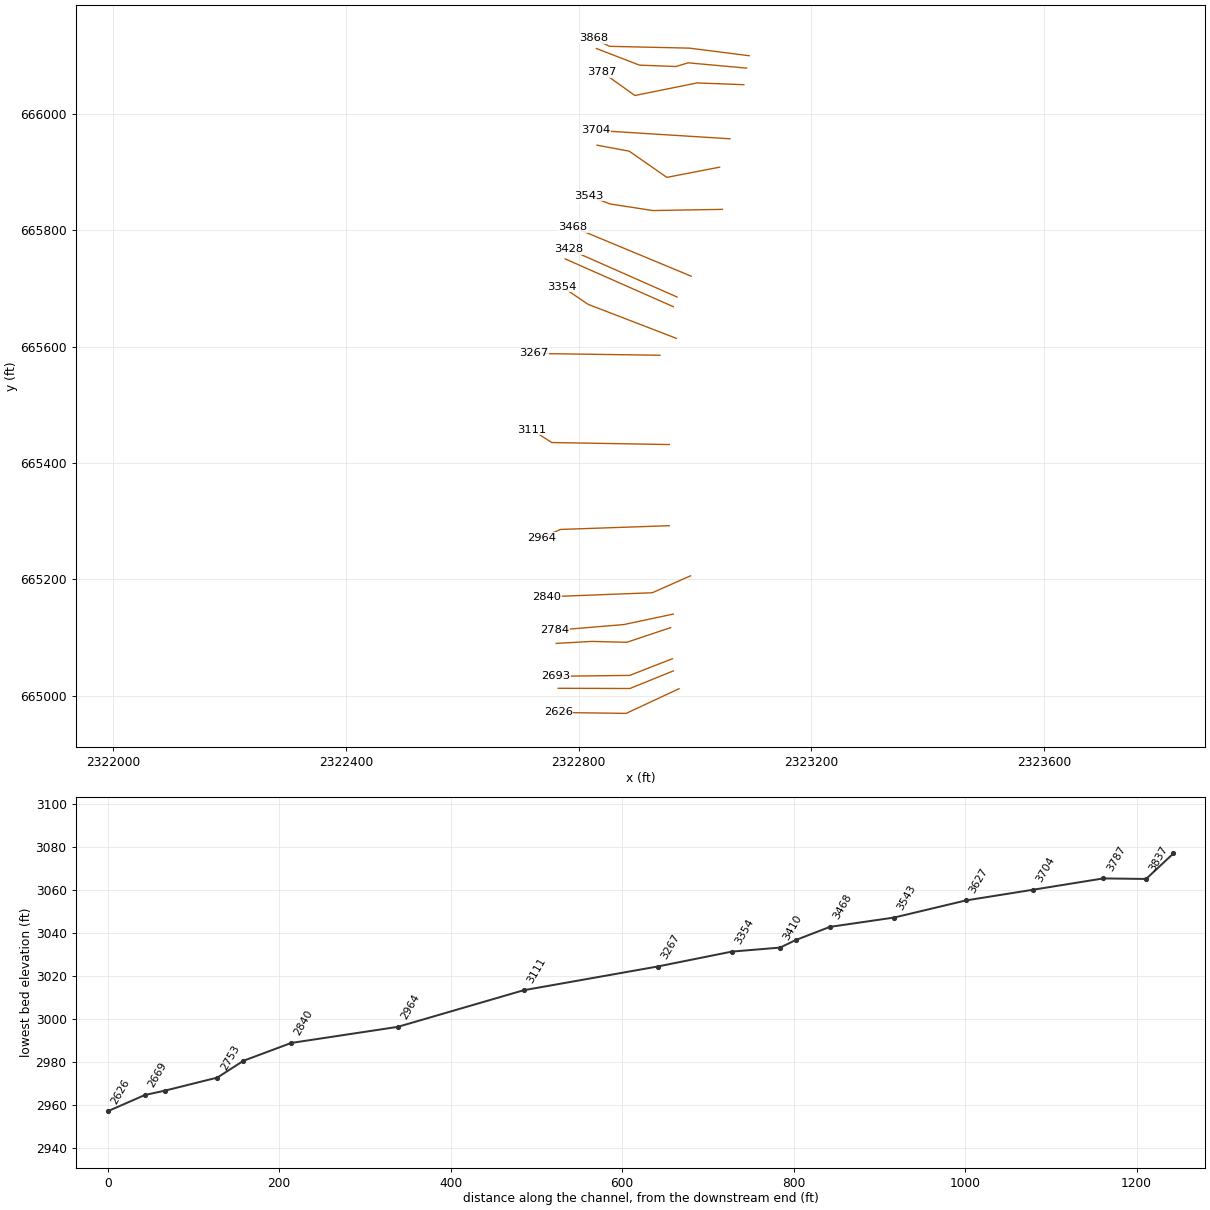
HEC-RAS study FSHHWKCKT1.prj: FSHHWKCKT1

--- FSHHWKCKT1.g01 (geometry) --- (continued)

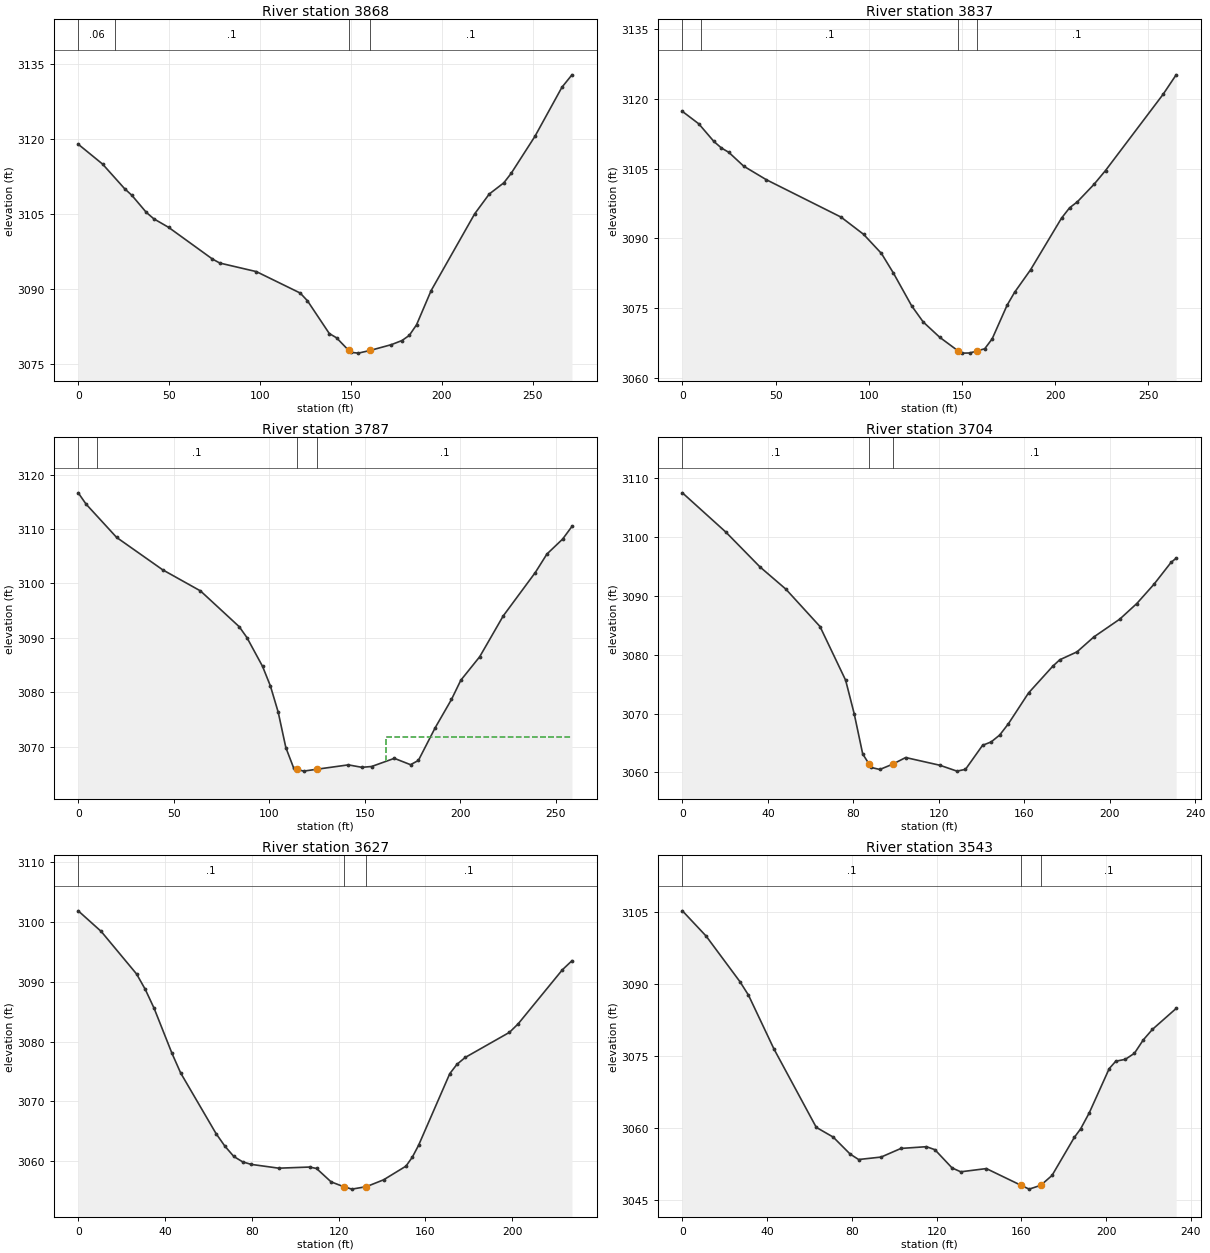
Type RM Length L Ch R = 1 ,3868    ,31.9,31.9,31.7
XS GIS Cut Line= 4
2323093.43299094666100.4244609482322990.65260502666113.486851132
2322853.15376097666116.5805751242322825.99773927666130.330459529
#Sta/Elev= 30
       0 3118.93    13.4 3114.96    25.5 3110.05    29.5 3108.72    37.5 3105.29
    41.6 3104.02    49.7 3102.32    73.8 3095.99    77.9 3095.18      98 3093.47
   122.1 3089.19   126.1 3087.64   138.1  3081.1   142.1 3080.24   148.8 3077.72
   150.1 3077.33   154.1 3077.18   160.5 3077.71   172.3 3078.88   178.1  3079.7
   182.1 3080.72   186.1 3082.84   194.1 3089.66   218.1 3105.03   226.1 3108.98
   234.1 3111.21   238.1 3113.08   251.2 3120.49   266.1 3130.33   271.6  3132.8
#Mann= 4 ,-1,0
       0     .06       0      20      .1       0   148.8    .045       0
   160.5      .1       0
Bank Sta=148.8,160.5
XS Rating Curve= 0 ,0
Exp/Cntr(USF)=0,0
Exp/Cntr=0.3,0.1

Type RM Length L Ch R = 1 ,3837    ,49.8,49.9,52.3
XS GIS Cut Line= 5
2323088.96427851 666079.112140122322988.59012236666088.221438538
2322967.27780153666081.8621170012322904.71582749666084.268346772
2322830.81019881666112.799356912
#Sta/Elev= 30
       0 3117.35     8.8 3114.67    16.9 3110.87    20.9 3109.48    24.9 3108.53
    32.9 3105.55      45 3102.64    85.1 3094.58    97.2 3090.87   106.8 3086.74
   113.2 3082.53     123 3075.46   129.2 3071.98   138.1 3068.67   147.8 3065.79
   150.2 3065.27   154.2  3065.3   158.2 3065.76   162.2 3066.21   166.2 3068.35
   174.2 3075.59   178.2 3078.36   186.8 3083.23   203.4 3094.35   207.7 3096.57
   211.9 3097.87   220.8 3101.62     227 3104.61   257.9 3121.03   264.9 3125.23
#Mann= 4 ,-1,0
       0     .06       0      10      .1       0   147.8    .045       0
   158.2      .1       0
Bank Sta=147.8,158.2
XS Rating Curve= 0 ,0
Exp/Cntr(USF)=0,0
Exp/Cntr=0.3,0.1

Type RM Length L Ch R = 1 ,3787    ,84.3,82.5,81.6
XS GIS Cut Line= 4
2323084.29496716666050.6156004772323003.85537794666053.653057336
2322896.97098486666032.023573551  2322840.778865666072.065324362
#Sta/Elev= 30
       0 3116.65     4.1 3114.58    20.1 3108.46    44.2 3102.51      64 3098.63
    84.3 3092.05    88.3 3090.07    96.5 3084.77   100.6 3081.18   104.7 3076.35
   108.7 3069.84   112.8 3066.09  114.333065.869     118 3065.52   124.8 3065.86
   141.4 3066.67   148.5 3066.22   153.6 3066.37   165.5 3067.87     174  3066.7
   178.1 3067.49   186.9  3073.5   195.4 3078.68   200.3 3082.22   210.2 3086.54
   222.5 3094.03   239.3 3102.01   245.4 3105.41   253.6 3108.15   258.5 3110.48
#Mann= 4 ,-1,0
       0     .06       0      10      .1       0  114.33    .045       0
   124.8      .1       0
#XS Ineff= 2 , 0
                          161.28         3071.76
Permanent Ineff=
       F       F
Bank Sta=114.33,124.8
XS Rating Curve= 0 ,0
Exp/Cntr(USF)=0,0
Exp/Cntr=0.3,0.1

Type RM Length L Ch R = 1 ,3704    ,80.4,77.6,74
XS GIS Cut Line= 2
2323060.43326837 665957.597536692322829.77895748665972.034915315
#Sta/Elev= 30
       0 3107.51    20.3 3100.85    36.3 3094.92    48.4 3091.15    64.4 3084.79
    76.4 3075.66    80.4 3069.98    84.4 3063.12    87.53061.345    88.4 3060.83
    92.4 3060.49    98.43061.387   104.5 3062.52   120.5 3061.21   128.5 3060.21
   132.5 3060.51   140.5  3064.6   144.5 3065.17   148.5 3066.34   152.6 3068.27
     162 3073.49   173.3 3078.02   176.6 3079.13   184.7 3080.48   192.6 3083.02
   204.7 3086.04   212.7  3088.7   220.7 3091.96   228.7 3095.68   231.1  3096.4
#Mann= 3 ,-1,0
       0      .1       0    87.5    .045       0    98.4      .1       0
Bank Sta=87.5,98.4
XS Rating Curve= 0 ,0
Exp/Cntr(USF)=0,0
Exp/Cntr=0.3,0.1

Type RM Length L Ch R = 1 ,3627    ,81.5,83.8,85.4
XS GIS Cut Line= 4
2323042.55841865665908.7854470522322951.80918157665891.254344435
2322887.18472487665936.2852158622322831.84144014665946.597629166
#Sta/Elev= 30
       0  3101.9    10.6 3098.44    26.9 3091.31    30.9 3088.73      35 3085.54
    43.2 3078.02    47.2 3074.73    63.5 3064.58    67.6 3062.46    71.7 3060.74
    75.8 3059.83    79.8 3059.41    92.4 3058.78   106.6 3058.97   109.8 3058.73
   116.5 3056.49   122.3 3055.68   126.1 3055.27   132.83055.686   140.7 3056.83
     151 3059.12   153.9  3060.6   156.8  3062.6   171.2 3074.62   174.5 3076.18
   178.3 3077.33   198.7 3081.54   202.7 3082.96   223.1 3092.03   227.5 3093.54
#Mann= 3 ,-1,0
       0      .1       0   122.3    .045       0   132.8      .1       0
Bank Sta=122.3,132.8
XS Rating Curve= 0 ,0
Exp/Cntr(USF)=0,0
Exp/Cntr=0.3,0.1

Type RM Length L Ch R = 1 ,3543    ,75.8,75,72.4
XS GIS Cut Line= 4
2323047.37087819665836.2548068152322927.87481823665834.194071261
2322854.62969922665845.4411119892322817.72257117665859.425963579
#Sta/Elev= 30
       0 3105.27    11.2 3100.01    27.2 3090.49    31.2  3087.7    43.2 3076.51
    63.2 3060.16    71.2 3058.13    79.2 3054.59    83.2 3053.46    93.8 3053.97
   103.2 3055.77   115.2 3056.13   119.2 3055.51   127.3 3051.71   131.4  3050.9
   143.5 3051.57   159.7 3048.12   163.7 3047.29  169.153048.078   174.5 3050.14
     185 3058.05     188 3059.84   192.1  3063.2   201.5  3072.4   204.6 3073.94
   209.1 3074.33   213.4 3075.59   217.6 3078.39   221.9 3080.57   233.1 3084.93
#Mann= 3 ,-1,0
       0      .1       0   159.7    .045       0  169.15      .1       0
Bank Sta=159.7,169.15
XS Rating Curve= 0 ,0
Exp/Cntr(USF)=0,0
Exp/Cntr=0.3,0.1

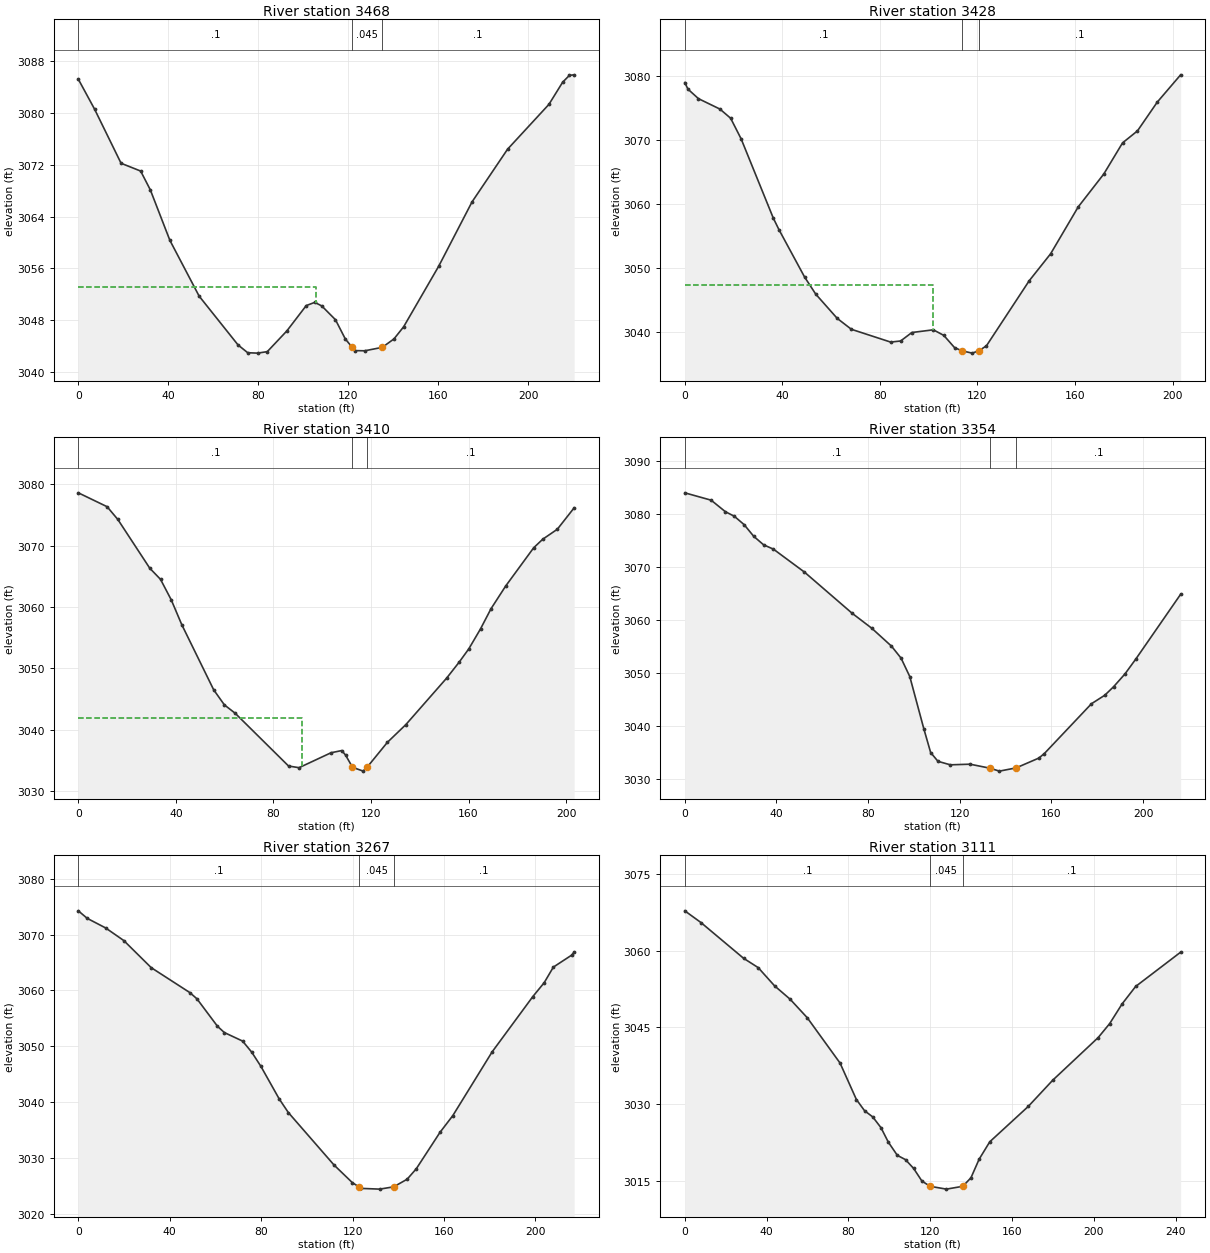
Type RM Length L Ch R = 1 ,3468    ,40,39.9,40.1
XS GIS Cut Line= 2
2322993.74632901665721.3286896632322790.24803981665805.890478754
#Sta/Elev= 30
       0 3085.17     7.2 3080.57      19 3072.21    27.7 3071.01      32 3068.11
    40.7 3060.32    53.7 3051.72      71 3044.19    75.3 3042.99    79.7 3042.93
      84 3043.16    92.7 3046.36   101.3 3050.26   105.1 3050.76   108.2 3050.21
   114.3 3048.08   118.7  3045.1   121.8  3043.8     123 3043.32   127.3 3043.29
   135.1 3043.82   140.3 3045.12   144.6 3046.99   160.2 3056.34     175 3066.25
   190.8 3074.38   209.2  3081.3   215.3 3084.72   218.3 3085.77   220.4 3085.85
#Mann= 3 ,-1,0
       0      .1       0   121.8    .045       0   135.1      .1       0
#XS Ineff= 2 , 0
          105.43 3053.13
Permanent Ineff=
       F       F
Bank Sta=121.8,135.1
XS Rating Curve= 0 ,0
Exp/Cntr(USF)=0,0
Exp/Cntr=0.3,0.1

Type RM Length L Ch R = 1 ,3428    ,18,18.1,18.2
XS GIS Cut Line= 2
2322969.34028419665685.5789902092322783.37309761 665767.73454953
#Sta/Elev= 30
       0 3078.91     1.3 3077.88     5.6  3076.4    14.4 3074.78    18.8 3073.35
    23.1 3070.14    36.3 3057.79    38.6 3056.01    49.1 3048.64    53.7 3045.96
    62.5 3042.19    68.3 3040.49    84.4  3038.5    88.5 3038.67    93.1 3039.99
   101.9 3040.41   106.2 3039.54   110.6 3037.64   113.63037.149   117.8 3036.78
   120.6 3037.14   123.7 3037.93   141.2 3048.04     150 3052.25   161.3 3059.54
   171.8 3064.67   179.5 3069.52   185.6 3071.38   193.7 3075.85   203.3 3080.11
#Mann= 3 ,-1,0
       0      .1       0   113.6    .045       0   120.6      .1       0
#XS Ineff= 2 , 0
          101.75 3047.41
Permanent Ineff=
       F       F
Bank Sta=113.6,120.6
XS Rating Curve= 0 ,0
Exp/Cntr(USF)=0,0
Exp/Cntr=0.3,0.1

Type RM Length L Ch R = 1 ,3410    ,55.9,56.3,56.3
XS GIS Cut Line= 2
2322962.98096265665668.9072553682322777.01377607665751.062814688
#Sta/Elev= 30
       0  3078.6    11.8 3076.34    16.2 3074.26    29.3 3066.32    33.7 3064.51
    38.1 3061.17    42.4 3057.14    55.5 3046.52    59.9 3044.06    64.3 3042.71
    86.2 3034.11    90.5 3033.84   103.6 3036.27     108 3036.63   109.6 3035.88
   112.4 3033.91   116.8 3033.28   118.43033.914   126.7 3037.96   134.3 3040.86
     151 3048.42   156.1    3051   160.1 3053.19   164.9 3056.44   169.2 3059.72
   175.2 3063.41   186.7 3069.65   190.4 3071.04   196.4 3072.67   203.3 3076.16
#Mann= 3 ,-1,0
       0      .1       0   112.4    .045       0   118.4      .1       0
#XS Ineff= 2 , 0
           91.53    3042
Permanent Ineff=
       F       F
Bank Sta=112.4,118.4
XS Rating Curve= 0 ,0
Exp/Cntr(USF)=0,0
Exp/Cntr=0.3,0.1

Type RM Length L Ch R = 1 ,3354    ,83.1,86.7,88.4
XS GIS Cut Line= 3
2322968.30019523 665614.421713862322816.66952554665672.858722582
2322771.98240122665703.032080026
#Sta/Elev= 30
       0 3083.96    11.5 3082.57    17.7  3080.4    21.6 3079.54    25.9 3077.95
    30.1 3075.74    34.4 3074.14    38.7 3073.32    52.2    3069      73 3061.23
    81.6 3058.39    90.2 3055.01    94.4 3052.74    98.2 3049.26   104.3 3039.44
   107.3 3034.92   110.5 3033.26   115.9  3032.6   124.5 3032.72     133 3031.98
   137.3 3031.41   144.6 3032.02   154.5 3033.87   156.9 3034.72   177.5 3044.14
   183.3 3045.74   187.2 3047.37   192.1 3049.76   196.9 3052.61   216.4  3064.8
#Mann= 3 ,-1,0
       0      .1       0     133    .045       0   144.6      .1       0
Bank Sta=133,144.6
XS Rating Curve= 0 ,0
Exp/Cntr(USF)=0,0
Exp/Cntr=0.3,0.1

Type RM Length L Ch R = 1 ,3267    ,155.9,156.2,155.6
XS GIS Cut Line= 2
2322940.03654395665585.3941801162322723.09392334665588.449709984
#Sta/Elev= 30
       0 3074.25     3.9  3072.9    11.9  3071.2    19.9 3068.93    31.9 3064.08
    48.8 3059.62    51.9 3058.51    60.9 3053.59    63.9 3052.47    71.9 3050.94
    75.9 3048.95    79.9 3046.42    87.9  3040.6    91.9 3038.16   111.9 3028.77
   119.9 3025.62     1233024.812   123.9 3024.58   131.9 3024.45     138 3024.86
   143.9 3026.22   147.9 3028.09   158.3 3034.62   163.9 3037.61   181.1 3049.01
   198.9  3058.9   203.9  3061.4   207.9 3064.18   215.9 3066.32     217 3066.87
#Mann= 3 ,-1,0
       0      .1       0     123    .045       0     138      .1       0
Bank Sta=123,138
XS Rating Curve= 0 ,0
Exp/Cntr(USF)=0,0
Exp/Cntr=0.3,0.1

Type RM Length L Ch R = 1 ,3111    ,146.3,146.8,147
XS GIS Cut Line= 3
2322956.07807575665431.8538042592322754.03116325665435.291275361
2322720.03839347665457.061925669
#Sta/Elev= 30
       0 3067.76     7.9 3065.47    28.7  3058.5    35.9 3056.66    43.9  3053.1
    51.5 3050.49    59.9 3046.86    75.9 3038.02    83.9 3030.89    87.9  3028.7
    91.9 3027.49    95.9  3025.4    99.5 3022.57   103.9 3019.99   107.9 3019.15
   111.9 3017.42   115.9 3014.98   119.9 3013.94   127.9 3013.39   135.9 3013.94
   139.9 3015.61   143.9 3019.24   149.1 3022.64   167.9 3029.54   179.9 3034.68
   202.1    3043   207.7 3045.72   213.8 3049.58   220.4 3052.98   242.4 3059.68
#Mann= 3 ,-1,0
       0      .1       0   119.9    .045       0   135.9      .1       0
Bank Sta=119.9,135.9
XS Rating Curve= 0 ,0
Exp/Cntr(USF)=0,0
Exp/Cntr=0.3,0.1

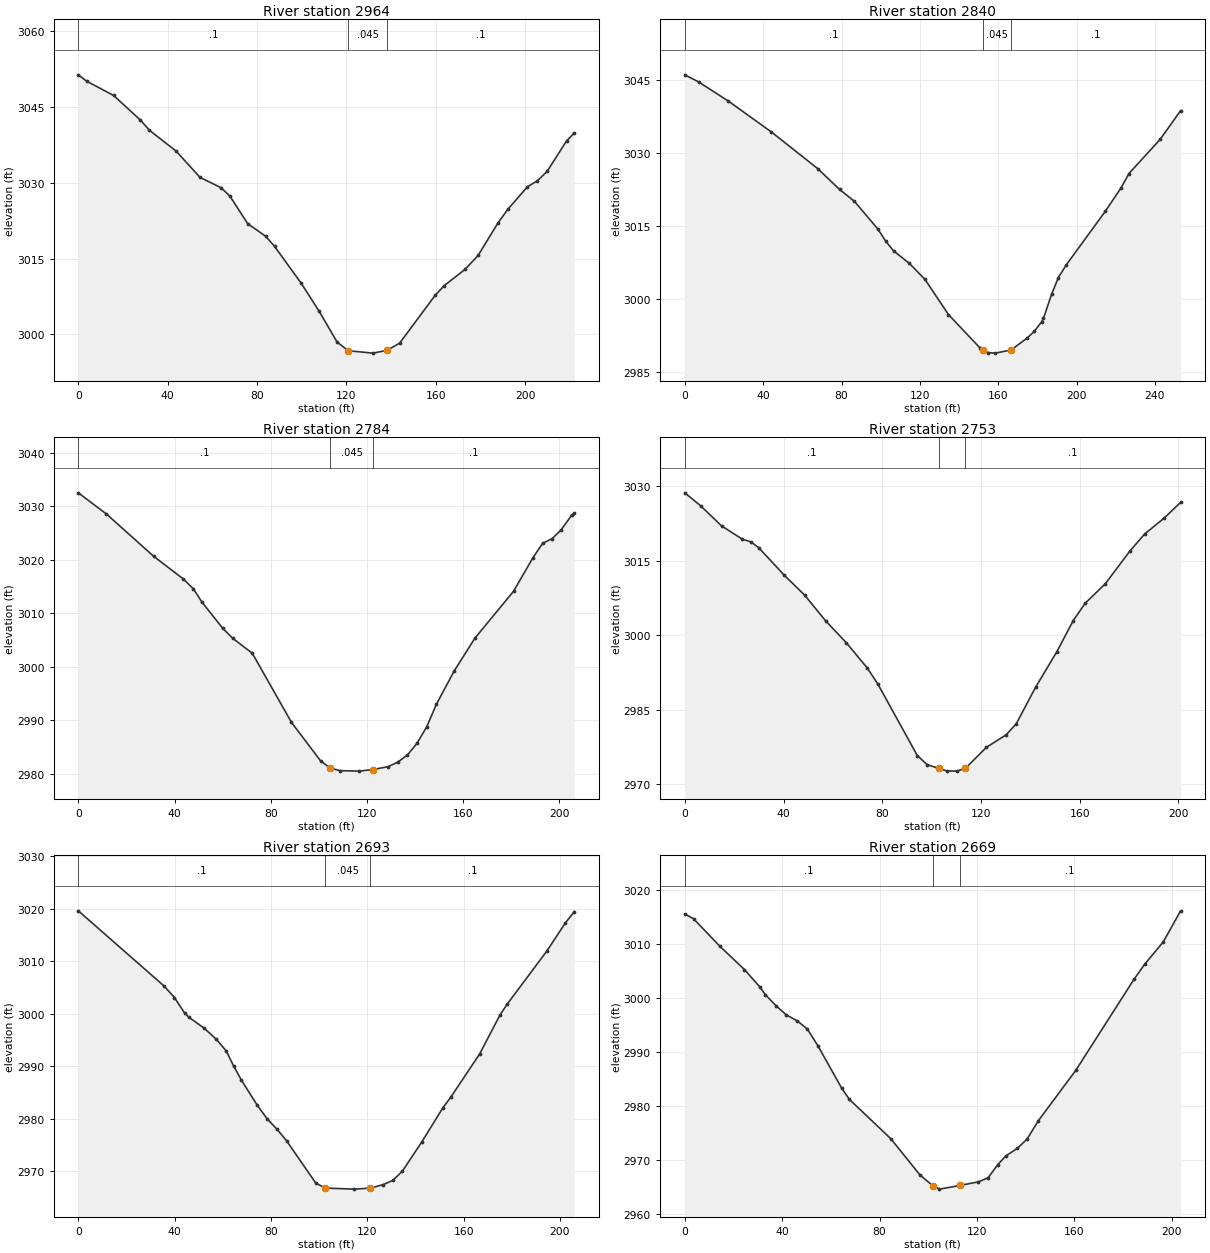
Type RM Length L Ch R = 1 ,2964    ,123,124.3,122.1
XS GIS Cut Line= 3
 2322955.9158919665292.2948293892322769.04935335665285.891303145
2322737.03172213 665271.91997316
#Sta/Elev= 30
       0 3051.28     3.7 3050.03    15.8  3047.2    27.8 3042.34    31.8 3040.34
    43.8  3036.2    54.5 3031.01    63.8 3029.01    67.8 3027.35    75.8 3021.89
    83.8 3019.41    87.8 3017.42    99.8 3010.08   107.8 3004.57   115.8 2998.51
   120.8 2996.79   131.8 2996.32   138.2 2996.88   143.8 2998.29   159.8  3007.8
   163.8 3009.66     173 3012.84   178.9  3015.6   187.9  3022.1   192.3 3024.77
     201 3029.17   205.4 3030.34   209.8 3032.21   218.5 3038.23   221.9 3039.77
#Mann= 3 ,-1,0
       0      .1       0   120.8    .045       0   138.2      .1       0
Bank Sta=120.8,138.2
XS Rating Curve= 0 ,0
Exp/Cntr(USF)=0,0
Exp/Cntr=0.3,0.1

Type RM Length L Ch R = 1 ,2840    ,55.2,55.8,55.2
XS GIS Cut Line= 3
2322992.59063311665206.1382944792322926.80895443665177.031357009
2322745.76380337665170.045692016
#Sta/Elev= 30
       0 3046.09     7.1 3044.62    22.3 3040.67    44.2 3034.33    67.8 3026.81
      79  3022.5    86.6 3020.06    98.6 3014.33   102.6 3011.84   106.6 3009.85
   114.6 3007.31   122.6 3003.99   134.6 2996.75   150.6 2989.93   152.32989.501
   154.6 2988.94   158.6 2988.82   166.6 2989.48   174.6 2991.88   178.4  2993.3
   182.2  2995.3   183.1 2995.99   187.2  3000.9   190.7 3004.38   194.7 3006.97
   214.7 3018.03   222.7 3022.83   226.7 3025.77   242.7 3032.83   253.1 3038.72
#Mann= 3 ,-1,0
       0      .1       0   152.3    .045       0   166.6      .1       0
Bank Sta=152.3,166.6
XS Rating Curve= 0 ,0
Exp/Cntr(USF)=0,0
Exp/Cntr=0.3,0.1

Type RM Length L Ch R = 1 ,2784    ,30.2,30.3,29.2
XS GIS Cut Line= 3
2322962.90155689665140.3566157982322877.90929948665122.310314566
2322759.15299461665112.413955827
#Sta/Elev= 30
       0 3032.55    11.7 3028.58    31.4 3020.64    43.7 3016.41    47.8  3014.6
    51.3 3012.17      60 3007.21    64.1 3005.36    72.3 3002.54    88.6  2989.6
   100.7  2982.4   104.7 2981.05   108.7 2980.57   116.7 2980.48   122.6 2980.78
   128.8 2981.32   132.8 2982.17   136.8  2983.5   140.8 2985.71   144.8 2988.76
   148.8 2992.95   156.2  2999.2   164.9 3005.39   180.9 3014.13     189 3020.43
     193  3023.1     197    3024   200.7 3025.62     205 3028.33   206.1  3028.7
#Mann= 3 ,-1,0
       0      .1       0   104.7    .045       0   122.6      .1       0
Bank Sta=104.7,122.6
XS Rating Curve= 0 ,0
Exp/Cntr(USF)=0,0
Exp/Cntr=0.3,0.1

Type RM Length L Ch R = 1 ,2753    ,60.3,60.6,60.3
XS GIS Cut Line= 4
2322958.27745416665117.0257754272322883.03503117665091.817654018
2322823.07025751665093.3454189522322761.57771892665089.907947851
#Sta/Elev= 30
       0 3028.63     6.4 3026.03    14.9 3021.98    23.3 3019.31    26.8 3018.76
      30 3017.57    40.2 3012.12    48.6 3008.04    57.1 3002.87    65.5 2998.46
    73.9 2993.43    78.2  2990.2    94.2 2975.81    98.2 2973.98     103 2973.21
   106.2  2972.7   110.2 2972.67   113.7 2973.23   122.2 2977.45   130.2 2979.97
   134.3 2982.19   142.2  2989.6   150.7 2996.64   157.4 3002.95   162.3 3006.47
   170.3  3010.3   180.4 3016.96   186.3 3020.34   194.3 3023.59   200.9  3026.7
#Mann= 3 ,-1,0
       0      .1       0     103    .045       0   113.7      .1       0
Bank Sta=103,113.7
XS Rating Curve= 0 ,0
Exp/Cntr(USF)=0,0
Exp/Cntr=0.3,0.1

Type RM Length L Ch R = 1 ,2693    ,22.4,24,24.3
XS GIS Cut Line= 3
2322961.33298403665063.554002741 2322888.0002672 665034.90841023
2322760.81383646665033.380645296
#Sta/Elev= 30
       0 3019.58    35.6 3005.28    39.9 3003.09    44.2  3000.1      46 2999.31
    52.1 2997.31    57.1 2995.24    61.4 2992.95    64.5 2990.05    67.6 2987.47
    74.2 2982.67    78.5 2979.95    82.6 2977.99    86.6 2975.76    98.6 2967.79
   102.6 2966.84   114.6 2966.64   121.3 2966.83   126.6  2967.5   130.6  2968.3
   134.6 2970.08   142.6  2975.6   151.4 2982.12   154.6 2984.09   166.6 2992.31
   175.1 2999.77     178 3001.77   194.6 3011.96   202.3 3017.32   205.9 3019.38
#Mann= 3 ,-1,0
       0      .1       0   102.6    .045       0   121.3      .1       0
Bank Sta=102.6,121.3
XS Rating Curve= 0 ,0
Exp/Cntr(USF)=0,0
Exp/Cntr=0.3,0.1

Type RM Length L Ch R = 1 ,2669    ,43.1,43.2,42.9
XS GIS Cut Line= 3
2322962.86074897  665042.54723492322888.38220844665012.373877455
2322765.01519003665012.755818689
#Sta/Elev= 30
       0 3015.59     3.6 3014.71    14.3 3009.65    24.5 3005.29    30.8 3002.06
    33.1 3000.62    37.4  2998.6    41.7 2996.87    46.3 2995.74    50.4 2994.22
    54.7 2991.12    64.5 2983.24    67.6  2981.2    84.6 2973.91    96.6 2967.18
   101.82965.198   104.6 2964.54     1132965.216   120.6 2965.89   124.6 2966.64
   128.6  2969.1   131.9  2970.7   136.6  2972.1   140.6 2973.81   145.2  2977.2
   160.6 2986.56   184.6 3003.52     189  3006.3   196.6 3010.44   203.7 3016.18
#Mann= 3 ,-1,0
       0      .1       0   101.8    .045       0     113      .1       0
Bank Sta=101.8,113
XS Rating Curve= 0 ,0
Exp/Cntr(USF)=0,0
Exp/Cntr=0.3,0.1

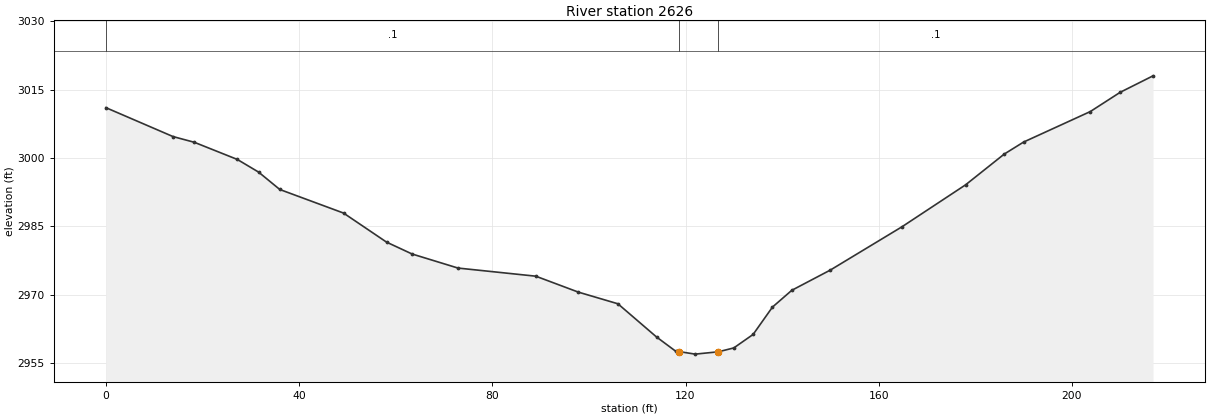
Type RM Length L Ch R = 1 ,2626    ,38.8,37.8,37.4
XS GIS Cut Line= 3
2322972.79122104665011.9919362222322881.88920747664969.596459306
2322765.39713126 664971.12422424
#Sta/Elev= 30
       0 3011.03    13.9 3004.69    18.3 3003.44    27.2 2999.68    31.6 2996.91
      36 2993.09    49.2 2987.92    58.1 2981.55    63.4 2978.94    72.9 2975.86
      89 2974.08    97.8 2970.59     106 2968.03     114 2960.75     118  2957.6
   118.7 2957.54     122 2956.99   126.8  2957.5     130 2958.35     134 2961.31
     138  2967.3     142 2970.98     150 2975.43   164.8  2984.9     178 2994.12
     186 3000.86     190 3003.49   203.8 3010.17     210  3014.4   216.8 3018.01
#Mann= 3 ,-1,0
       0      .1       0   118.7    .045       0   126.8      .1       0
Bank Sta=118.7,126.8
XS Rating Curve= 0 ,0
Exp/Cntr(USF)=0,0
Exp/Cntr=0.3,0.1