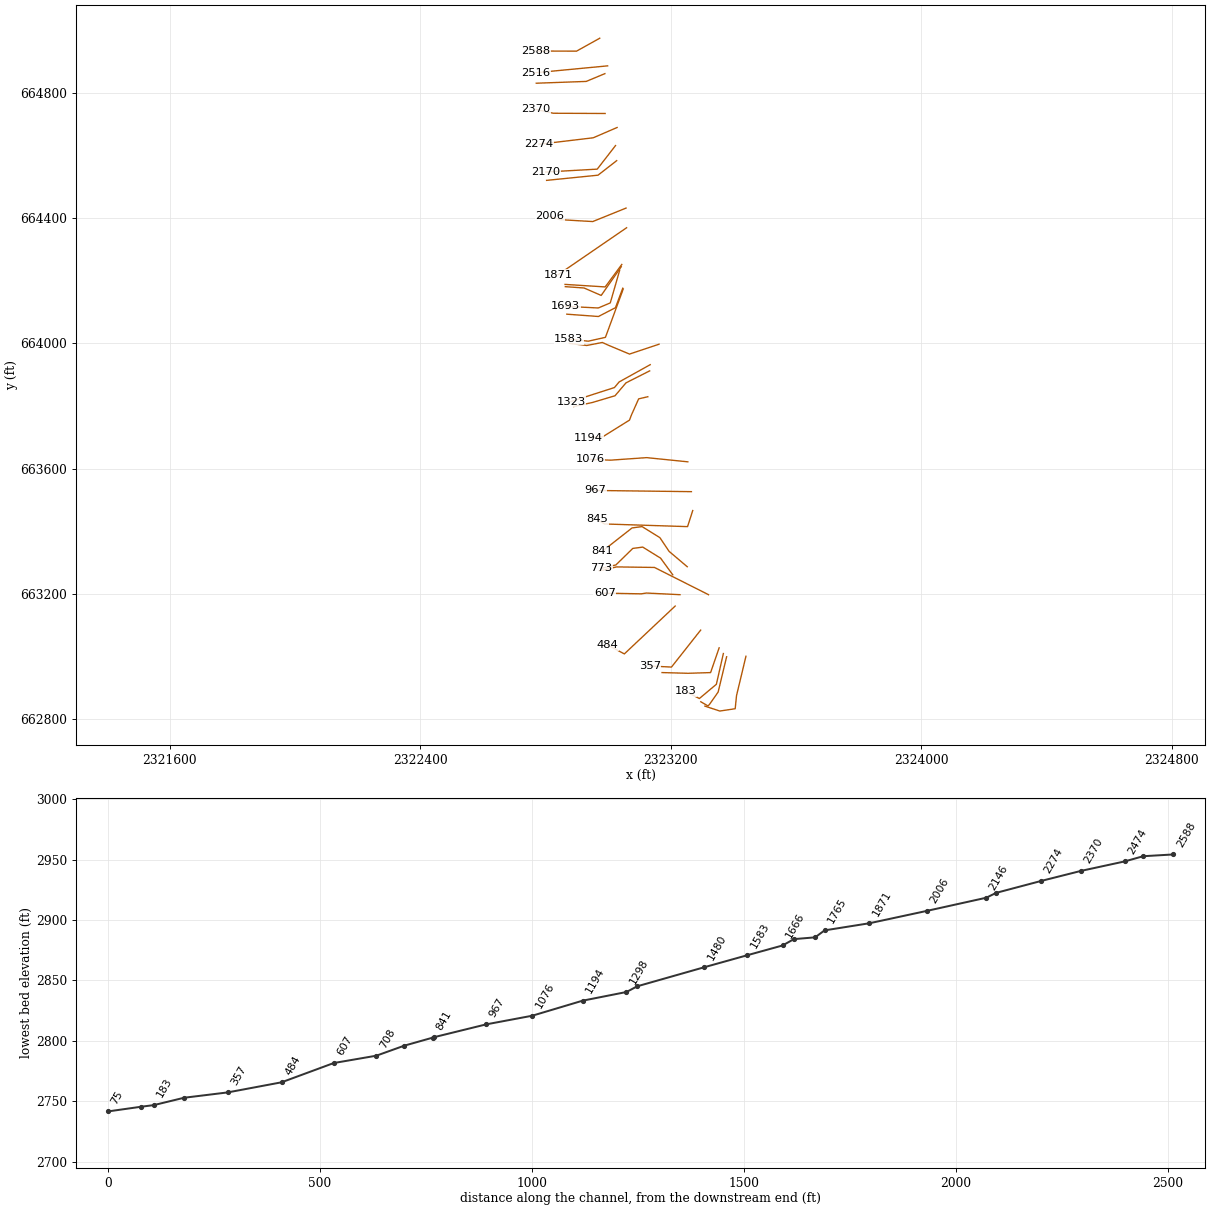
HEC-RAS study FSHHWKCKT1.prj: FSHHWKCKT1

--- FSHHWKCKT1.g01 (geometry) --- (continued)

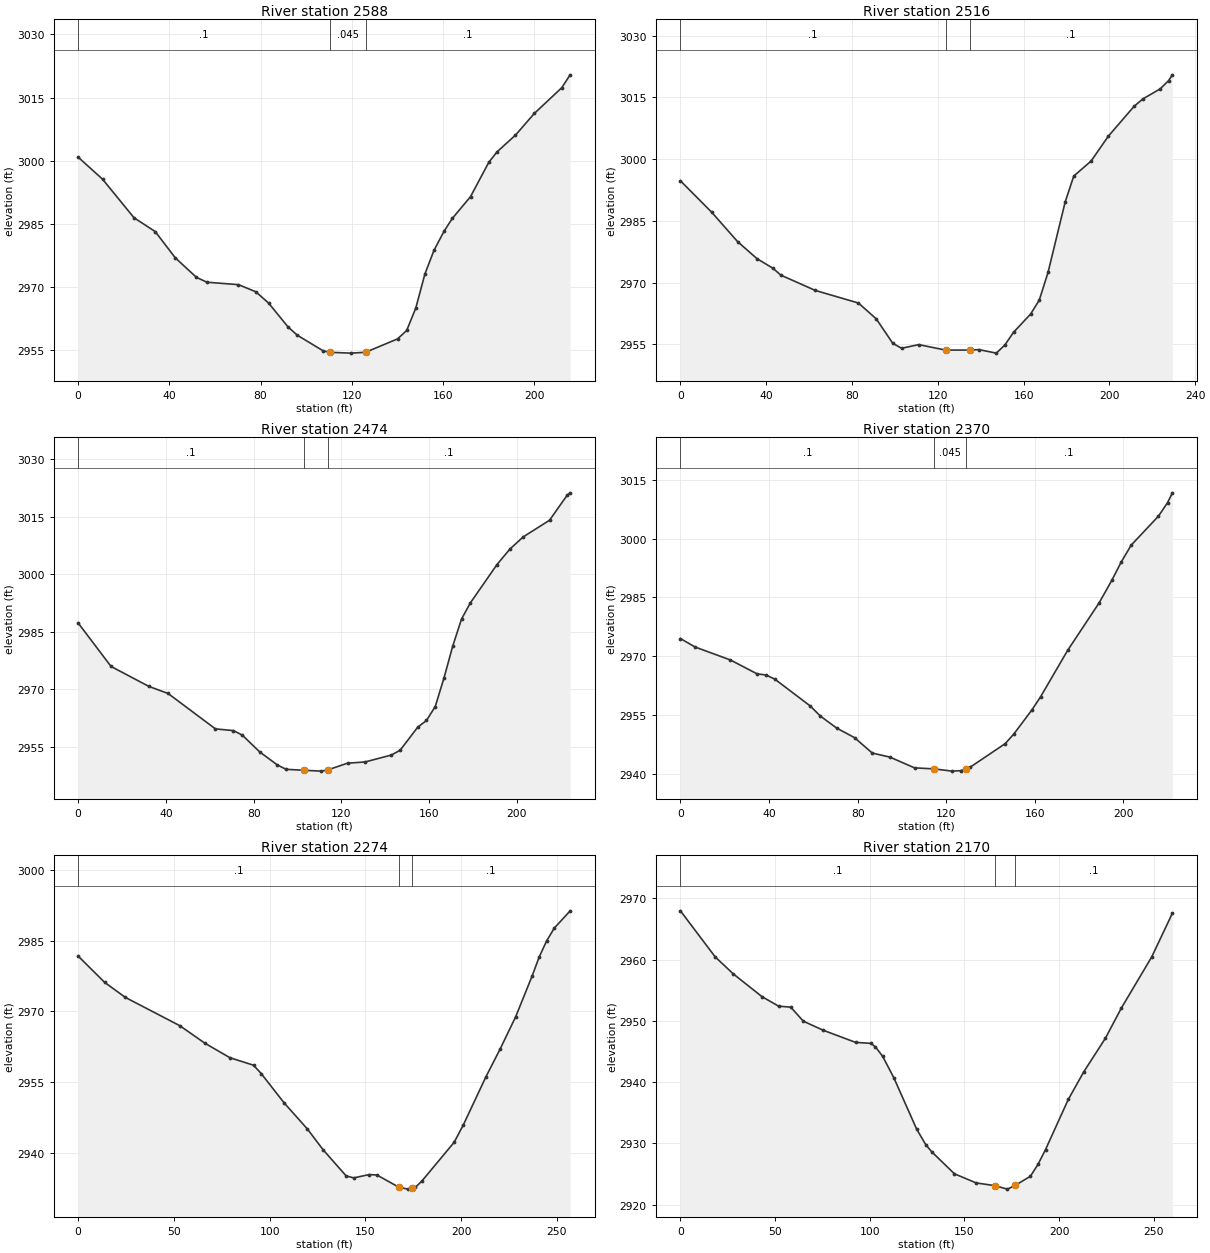
Type RM Length L Ch R = 1 ,2588    ,68.6,71.5,69.8
XS GIS Cut Line= 3
 2322973.5551035664973.7978128742322899.45850421664932.548159659
2322768.45266113664932.930100892
#Sta/Elev= 30
       0 3000.85    10.7 2995.62    24.5 2986.46    33.8 2983.18    42.6 2976.95
    51.9  2972.3    56.5 2971.15    70.3 2970.57    77.9 2968.89    83.5 2966.22
    92.1 2960.51    96.1 2958.58   107.5 2954.84  110.382954.507   119.6 2954.31
  126.082954.513   140.1 2957.69   144.1 2959.69   148.1 2965.02   152.1 2973.11
   156.1 2978.75   160.5 2983.26   164.1 2986.29   172.1 2991.47   180.1 2999.61
   183.7 3002.09   191.8 3006.07   200.1 3011.24   212.1 3017.33   215.8  3020.4
#Mann= 3 ,-1,0
       0      .1       0  110.38    .045       0  126.08      .1       0
Bank Sta=110.38,126.08
XS Rating Curve= 0 ,0
Exp/Cntr(USF)=0,0
Exp/Cntr=0.3,0.1

Type RM Length L Ch R = 1 ,2516    ,43.5,42.4,43
XS GIS Cut Line= 2
2322998.76322491664885.5693879422322770.36236729664863.798737634
#Sta/Elev= 30
       0 2994.75    14.7 2987.03    26.7 2979.93    35.7 2975.81    43.1 2973.49
    46.8 2971.81    62.9 2968.08      83 2965.02    91.3 2961.18      99 2955.24
   103.1 2954.02   111.1 2954.91   123.62953.582   134.8 2953.58   139.2 2953.69
   147.3 2952.84   151.3 2954.84   155.3 2957.89   163.3 2962.36   167.3 2965.71
   171.4 2972.46   179.4 2989.61   183.4 2995.89   191.5 2999.55   199.5 3005.57
   211.5 3012.83   215.6 3014.64   223.6 3017.05   227.6 3019.08   229.4  3020.5
#Mann= 3 ,-1,0
       0      .1       0   123.6    .045       0   134.8      .1       0
Bank Sta=123.6,134.8
XS Rating Curve= 0 ,0
Exp/Cntr(USF)=0,0
Exp/Cntr=0.3,0.1

Type RM Length L Ch R = 1 ,2474    ,104.3,104.3,104.4
XS GIS Cut Line= 3
2322989.97857654664860.7432077662322930.39574412 664835.91702759
2322770.74430853664830.187909088
#Sta/Elev= 30
       0 2987.29      15 2975.94    32.3 2970.72      41 2968.89    62.6 2959.65
    70.8  2959.2    74.8 2958.04    82.8 2953.63    90.8 2950.25    94.8  2949.1
   102.8 2948.86   110.8 2948.63   113.8 2948.95   122.8  2950.7   130.8 2951.02
   142.8 2952.83   146.8 2954.08   154.8 2960.09   158.8 2961.84   162.8 2965.49
   166.8 2972.96   170.8 2981.32   174.8 2988.34   178.8 2992.52   190.9 3002.49
   196.8 3006.55   202.9 3009.74   214.9 3014.09   222.9 3020.59   224.3 3021.24
#Mann= 3 ,-1,0
       0      .1       0   102.8    .045       0   113.8      .1       0
Bank Sta=102.8,113.8
XS Rating Curve= 0 ,0
Exp/Cntr(USF)=0,0
Exp/Cntr=0.3,0.1

Type RM Length L Ch R = 1 ,2370    ,93.8,95.2,93.7
XS GIS Cut Line= 3
2322990.74245901664733.5567770192322824.97996368664734.320659486
2322769.98042606664746.542778957
#Sta/Elev= 30
       0  2974.5     6.6 2972.34    22.6 2969.02    34.6 2965.49    38.6  2965.2
    42.6 2964.15    58.6  2957.3    63.2 2954.71    70.6 2951.64    78.6 2949.22
    86.6 2945.29    94.6 2944.25   105.7 2941.51   114.6 2941.25   122.6 2940.68
   126.6  2940.8   128.82941.254   130.6 2941.61   146.6 2947.69   150.6 2950.21
   158.6 2956.24   162.6 2959.66   174.8 2971.48     189 2983.59   194.7  2989.3
     199 2994.03   203.5 2998.33   215.8 3005.72   219.9 3009.16   222.1 3011.66
#Mann= 3 ,-1,0
       0      .1       0   114.6    .045       0   128.8      .1       0
Bank Sta=114.6,128.8
XS Rating Curve= 0 ,0
Exp/Cntr(USF)=0,0
Exp/Cntr=0.3,0.1

Type RM Length L Ch R = 1 ,2274    ,103.4,104.6,101.9
XS GIS Cut Line= 3
2323028.93658236664688.869652702 2322952.9302769664656.022706623
2322779.91089813664635.397880016
#Sta/Elev= 30
       0 2981.76    13.9 2976.15    24.7 2972.97    53.1 2966.97    66.2 2963.25
    79.3 2960.16    91.6 2958.58    95.6 2956.81   107.6 2950.57   119.8    2945
   127.9 2940.64     140 2935.05     144 2934.64     152 2935.34   156.1 2935.25
   167.4 2932.68   172.2 2932.25   174.4 2932.46   176.2 2932.65   179.6 2933.99
   196.4  2942.2   201.2 2945.89     213 2956.11   220.5 2962.08   228.6 2968.92
   237.2 2977.59   240.8 2981.54   244.7 2984.98   248.7 2987.69     257 2991.37
#Mann= 3 ,-1,0
       0      .1       0   167.4    .045       0   174.4      .1       0
Bank Sta=167.4,174.4
XS Rating Curve= 0 ,0
Exp/Cntr(USF)=0,0
Exp/Cntr=0.3,0.1

Type RM Length L Ch R = 1 ,2170    ,23.2,23.5,23.8
XS GIS Cut Line= 3
2323023.97134632664631.196526447 2322965.5343376664555.954103453
2322801.29960721 664546.78751385
#Sta/Elev= 30
       0 2967.95    18.4 2960.42    27.9 2957.66    43.1 2953.94    51.8  2952.4
    58.3 2952.22    64.9 2949.94    75.4 2948.46    92.5 2946.48   100.6 2946.32
     103 2945.74   106.8  2944.2   112.7  2940.7   124.7 2932.35   129.5 2929.81
   132.7 2928.62   144.7 2925.03   156.1 2923.55   165.9  2923.1   172.7 2922.53
   176.8 2923.14   184.8 2924.63   188.8 2926.56   192.8 2928.99   204.8 2937.16
     213 2941.68   224.4 2947.15   232.8 2952.07   248.9 2960.45   259.8 2967.57
#Mann= 3 ,-1,0
       0      .1       0   165.9    .045       0   176.8      .1       0
Bank Sta=165.9,176.8
XS Rating Curve= 0 ,0
Exp/Cntr(USF)=0,0
Exp/Cntr=0.3,0.1

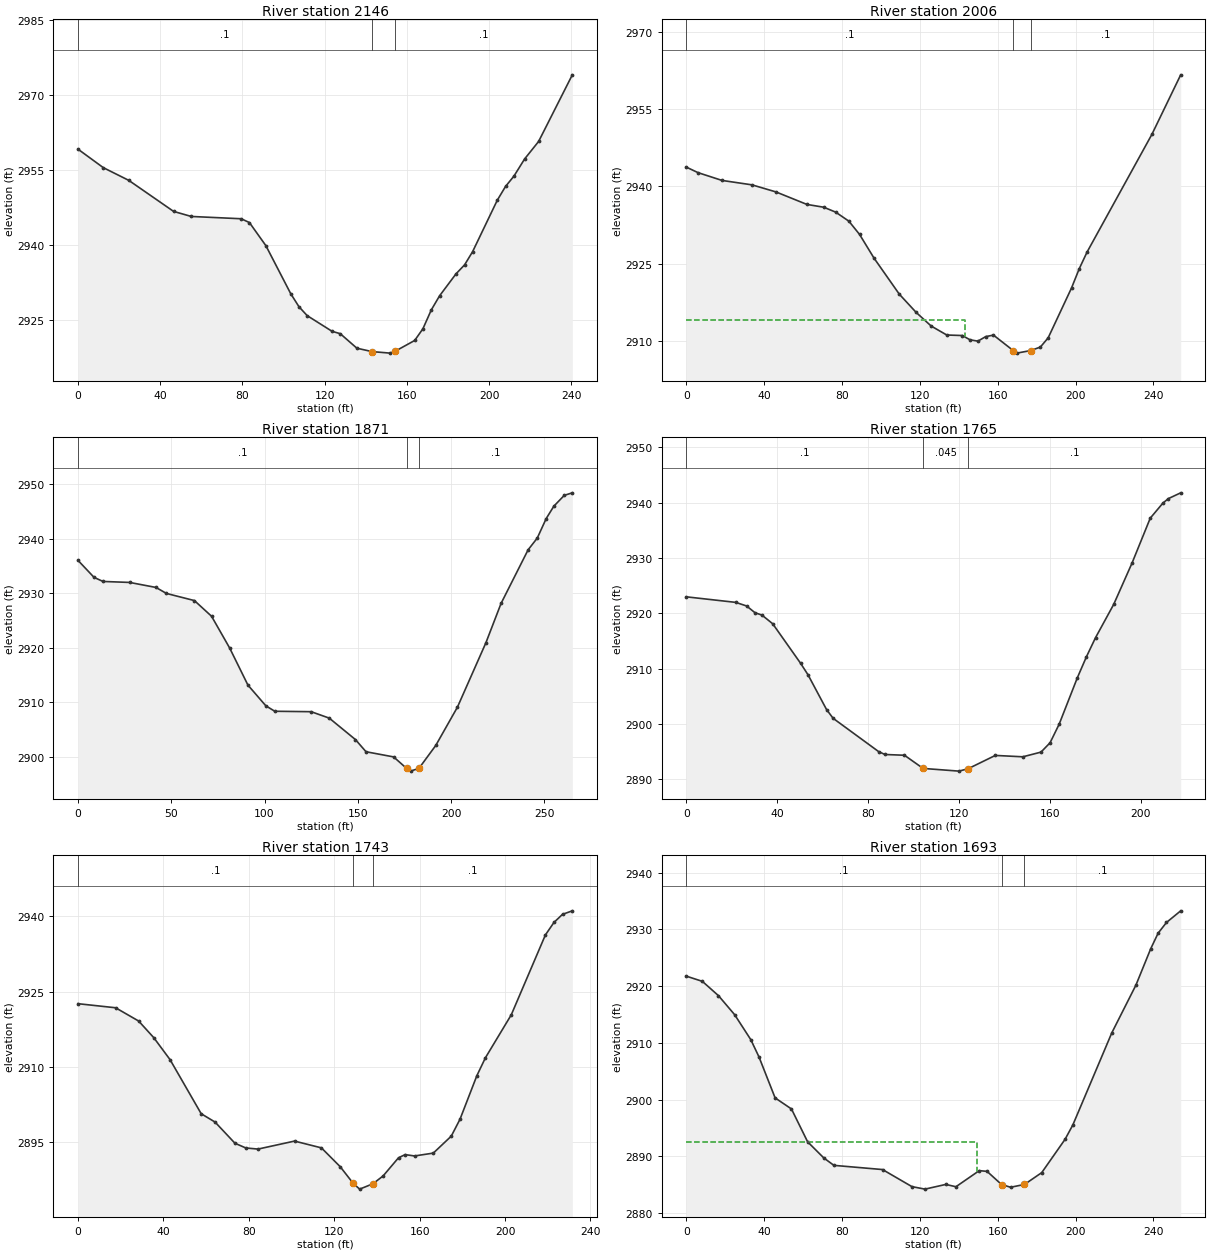
Type RM Length L Ch R = 1 ,2146    ,140.1,140.1,138.3
XS GIS Cut Line= 3
2323027.64400036664582.9919525352322968.00318926664536.632498528
2322803.86566291664520.093450071
#Sta/Elev= 30
       0 2959.22    12.3 2955.53    24.7 2952.99    46.5 2946.79    55.1 2945.78
    79.4 2945.32    83.4 2944.56    91.4 2939.95   103.5 2930.35   107.5 2927.75
   111.5 2925.97   123.6 2922.84   127.6 2922.36   135.7 2919.46     143 2918.79
   151.8 2918.48   154.32918.855   163.8 2921.01   167.8 2923.34   171.9 2927.12
   175.9 2929.92   183.9 2934.31   188.1 2936.12     192 2938.76     204 2949.03
     208 2951.77   212.1 2953.84   217.3 2957.27   224.1 2960.76   240.5 2974.07
#Mann= 3 ,-1,0
       0      .1       0     143    .045       0   154.3      .1       0
Bank Sta=143,154.3
XS Rating Curve= 0 ,0
Exp/Cntr(USF)=0,0
Exp/Cntr=0.3,0.1

Type RM Length L Ch R = 1 ,2006    ,132.5,135.2,136.9
XS GIS Cut Line= 4
2323057.55653702664431.6333625032322951.13243172664388.596224315
 2322848.0770481664394.6117987422322813.77108651664405.336708578
#Sta/Elev= 30
       0 2943.73       6 2942.66    18.3 2941.15    33.7 2940.29      46 2938.92
    61.9 2936.49    70.6 2935.94    76.7 2934.99    83.5 2933.23      89 2930.65
    96.4 2926.06   109.4 2919.05   118.1 2915.49   125.8 2912.85   133.8 2911.11
   141.8 2911.01   145.8 2910.17   149.8 2909.92   153.8  2910.8   157.8 2911.09
     1682908.072   169.8 2907.59   176.9 2908.09   181.9 2908.77   185.9 2910.56
   197.9 2920.25   201.9 2924.02   205.9 2927.24   239.2  2950.1     254 2961.67
#Mann= 3 ,-1,0
       0      .1       0     168    .045       0   176.9      .1       0
#XS Ineff= 2 , 0
          143.13 2914.07
Permanent Ineff=
       F       F
Bank Sta=168,176.9
XS Rating Curve= 0 ,0
Exp/Cntr(USF)=0,0
Exp/Cntr=0.3,0.1

Type RM Length L Ch R = 1 ,1871    ,112.5,106,99.7
XS GIS Cut Line= 2
 2323059.2398788664368.8229875042322840.68461743664219.017148152
#Sta/Elev= 30
       0 2936.07     8.6 2932.95    13.4  2932.2    27.7 2932.02    41.8  2931.1
    47.4    2930    62.4 2928.69    71.6 2925.81    81.3 2919.98    91.1 2913.17
   100.7 2909.37   105.5 2908.37     125 2908.29   134.7 2907.11   148.7 2903.18
   154.4 2900.94   169.2 2899.99   176.2 2897.87   178.3 2897.38   182.8  2897.9
   191.8  2902.1   203.4 2909.12   218.7 2920.97   226.8 2928.17   241.3 2938.01
   246.2 2940.16     251 2943.75   255.1 2946.02   260.7 2948.01     265 2948.47
#Mann= 3 ,-1,0
       0      .1       0   176.2    .045       0   182.8      .1       0
Bank Sta=176.2,182.8
XS Rating Curve= 0 ,0
Exp/Cntr(USF)=0,0
Exp/Cntr=0.3,0.1

Type RM Length L Ch R = 1 ,1765    ,25.9,22.2,19.4
XS GIS Cut Line= 3
2323043.96222947664251.6943425712322990.91483593664179.974266508
2322862.75233314664188.037470325
#Sta/Elev= 30
       0 2922.98    21.7 2921.98    26.5 2921.33    30.2 2920.11    33.3 2919.67
      38 2918.11    50.3 2910.95    53.5 2908.91    61.7  2902.6    64.6 2901.01
    84.6    2895    87.4 2894.47      96 2894.33   104.2 2891.95     120 2891.46
     124 2891.89     136  2894.3   148.1 2894.05   156.1  2894.9   160.1 2896.59
   164.1 2899.95   172.1 2908.34   176.1 2912.14   180.1 2915.59   188.1 2921.61
   196.2 2929.11   204.2 2937.21   209.8 2939.95   212.2 2940.75   217.6 2941.79
#Mann= 3 ,-1,0
       0      .1       0   104.2    .045       0     124      .1       0
Bank Sta=104.2,124
XS Rating Curve= 0 ,0
Exp/Cntr(USF)=0,0
Exp/Cntr=0.3,0.1

Type RM Length L Ch R = 1 ,1743    ,48.3,50.1,51.5
XS GIS Cut Line= 4
2323042.26471287 664244.479897052322978.18346148664152.814001016
2322923.43855135664176.5792333212322863.60109144664180.823024804
#Sta/Elev= 30
       0  2922.6    17.6 2921.79    28.4 2919.15    35.5 2915.83    43.1 2911.47
    57.7  2900.7    64.2 2899.04    73.5 2894.83    78.6 2893.89    84.3 2893.67
   101.4 2895.26     114 2893.91   122.8 2890.16   128.9 2886.84   131.9  2885.7
   138.1 2886.76   142.9 2888.33   150.1 2891.94   153.2 2892.57   157.6  2892.3
   166.4 2892.87   174.8 2896.24   178.9 2899.61   186.8 2908.28   190.8 2911.84
   202.9 2920.38   218.9 2936.29   222.9 2938.77   226.9 2940.38   231.5 2941.08
#Mann= 3 ,-1,0
       0      .1       0   128.9    .045       0   138.1      .1       0
Bank Sta=128.9,138.1
XS Rating Curve= 0 ,0
Exp/Cntr(USF)=0,0
Exp/Cntr=0.3,0.1

Type RM Length L Ch R = 1 ,1693    ,27.5,26.8,26.8
XS GIS Cut Line= 5
2323037.17216309664233.0216600462323007.16557923664128.967775341
2322969.35432525664112.9546191952322966.13640192664112.907884028
2322864.87422888664118.014910855
#Sta/Elev= 30
       0 2921.77     8.2 2920.86    16.5 2918.33    24.8 2914.98    33.1 2910.58
    37.3 2907.54    45.6 2900.31      54 2898.36    62.3 2892.57    70.6 2889.73
    75.8 2888.42   100.8 2887.68   115.9 2884.67   122.6 2884.23   133.3 2885.06
   138.5 2884.65   150.5 2887.49   154.5 2887.36161.95722885.041   166.6 2884.56
173.72722885.053   182.6 2887.14   194.6 2893.02   198.6 2895.56   218.6 2911.78
     231  2920.2   238.6 2926.61   242.4 2929.35   246.7 2931.24     254 2933.29
#Mann= 3 ,-1,0
       0      .1       0161.9572    .045       0173.7272      .1       0
#XS Ineff= 2 , 0
          149.58 2892.51
Permanent Ineff=
       F       F
Bank Sta=161.9572,173.7272
XS Rating Curve= 0 ,0
Exp/Cntr(USF)=0,0
Exp/Cntr=0.3,0.1

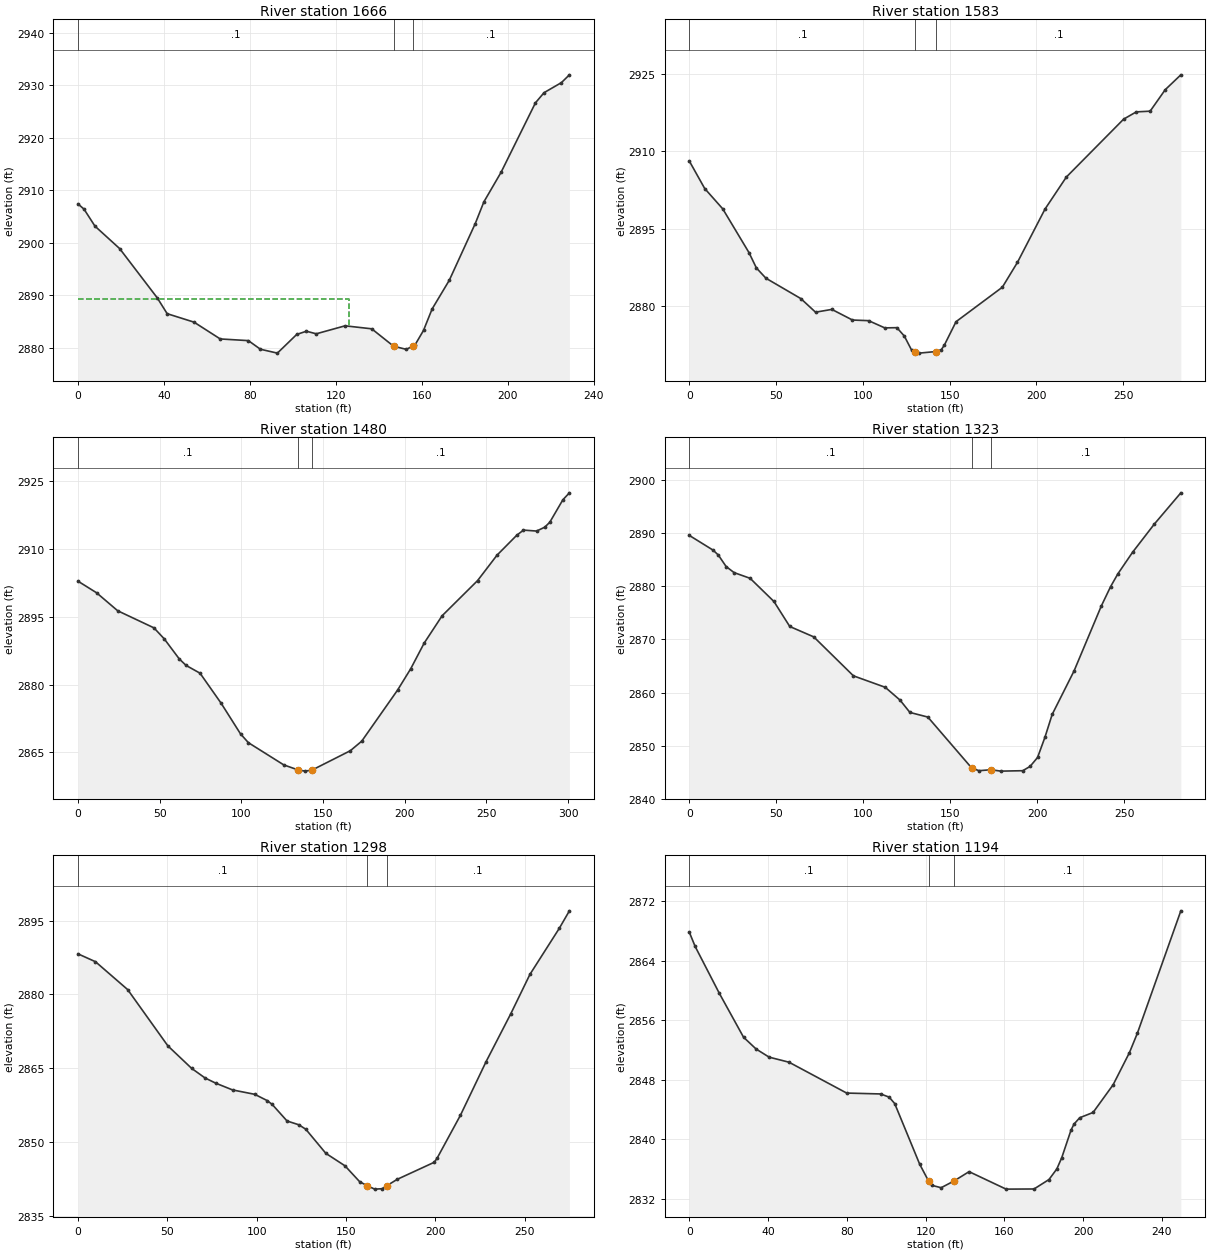
Type RM Length L Ch R = 1 ,1666    ,78.6,83.1,90
XS GIS Cut Line= 4
  2323046.942711664175.7859996852323023.81269607664113.749010817
2322969.34246419 664085.573341222322868.44304957664092.976541105
#Sta/Elev= 30
       0 2907.37     2.8 2906.38     7.9 2903.14    19.4 2898.86    36.9 2889.48
    41.5 2886.47      54 2884.86    66.2 2881.66    79.3 2881.34    84.9  2879.7
    92.8 2878.96   101.8 2882.52   106.3 2883.13   110.9 2882.64   124.3 2884.16
   136.7 2883.59   146.9 2880.27   152.8 2879.68155.71982880.271   156.8 2880.49
   160.8 2883.28   164.8 2887.36   172.8 2892.83   184.9 2903.64   188.9 2907.76
   196.9 2913.39   212.9 2926.62   216.9 2928.55     225 2930.47   228.7 2931.95
#Mann= 3 ,-1,0
       0      .1       0   146.9    .045       0155.7198      .1       0
#XS Ineff= 2 , 0
          126.34 2889.35
Permanent Ineff=
       F       F
Bank Sta=146.9,155.7198
XS Rating Curve= 0 ,0
Exp/Cntr(USF)=0,0
Exp/Cntr=0.3,0.1

Type RM Length L Ch R = 1 ,1583    ,108.9,102.4,92.1
XS GIS Cut Line= 4
2323048.57551562664173.3899000312322991.69121259664019.025447769
2322936.81164271664006.7464572482322874.66491518664013.512431616
#Sta/Elev= 30
       0 2908.07     8.8 2902.79    19.2 2898.85    34.3 2890.39    38.6  2887.4
    44.1 2885.41    64.2 2881.47    72.7 2878.83    82.1 2879.37      94 2877.31
   103.3 2877.19   112.6 2875.79   119.6 2875.83   123.9  2874.2   128.1 2871.47
   130.12871.168   132.4  2870.9   142.12871.206   145.2 2871.57   146.9 2872.41
   153.7 2876.99   180.4 2883.67   189.1 2888.48     205 2898.81   217.3 2905.01
   250.3 2916.22   257.6 2917.63   265.6 2917.77   274.3 2921.93   283.3 2924.81
#Mann= 3 ,-1,0
       0      .1       0   130.1    .045       0   142.1      .1       0
Bank Sta=130.1,142.1
XS Rating Curve= 0 ,0
Exp/Cntr(USF)=0,0
Exp/Cntr=0.3,0.1

Type RM Length L Ch R = 1 ,1480    ,151.3,157.1,159.1
XS GIS Cut Line= 6
 2323162.9762726663997.1765377022323068.61769087663965.620552992
2322999.00890107663994.7703079312322981.82154557664002.676491464
 2322931.9782146 663993.051572382322876.29118276663999.926514583
#Sta/Elev= 30
       0 2902.86    11.4 2900.29    24.3 2896.32    46.5 2892.54    52.8 2890.11
      62 2885.67    66.2 2884.23    74.7 2882.52    87.6 2875.89    99.5  2869.1
   104.3 2867.16     126 2862.24   134.7 2861.14     139 2860.87   143.3 2861.11
   166.7 2865.38   173.7  2867.5   195.6 2878.77   203.7 2883.52   211.9 2889.17
   222.9 2895.22   244.6 2902.99   256.5 2908.61   268.6 2913.02   272.7 2914.15
   280.7 2913.94   285.7 2914.79   288.8 2915.89   296.8 2920.85   300.8 2922.39
#Mann= 3 ,-1,0
       0      .1       0   134.7    .045       0   143.3      .1       0
Bank Sta=134.7,143.3
XS Rating Curve= 0 ,0
Exp/Cntr(USF)=0,0
Exp/Cntr=0.3,0.1

Type RM Length L Ch R = 1 ,1323    ,25.7,25.5,25.6
XS GIS Cut Line= 4
 2323134.6481157663931.7625534952323035.34339499663876.593264215
 2323020.4901248663858.769339986 2322881.7181433663814.209529414
#Sta/Elev= 30
       0  2889.6    13.6 2886.84    16.6 2885.92    21.1 2883.75    25.7  2882.6
    34.9 2881.53    48.6 2877.16    57.7 2872.45    71.5 2870.49    94.3 2863.15
   112.6 2860.99   121.1 2858.58   126.8 2856.25   137.1 2855.38   162.3 2845.79
   166.5 2845.27   173.3 2845.45   179.1 2845.19   191.7 2845.27   195.9 2846.08
   200.2 2847.76   204.4 2851.53   208.6 2855.87   221.2 2864.08   236.9 2876.34
   242.2 2879.96   246.4 2882.38   254.8 2886.42   267.4 2891.77   282.6 2897.64
#Mann= 3 ,-1,0
       0      .1       0   162.3    .045       0   173.3      .1       0
Bank Sta=162.3,173.3
XS Rating Curve= 0 ,0
Exp/Cntr(USF)=0,0
Exp/Cntr=0.3,0.1

Type RM Length L Ch R = 1 ,1298    ,100.5,103.3,103
XS GIS Cut Line= 5
2323132.94697984 663911.993241142323057.40749144663873.799117792
2323022.35087838663832.6053863122322950.11816937663811.099766801
2322890.62648615663798.259629393
#Sta/Elev= 30
       0 2888.25     9.8 2886.65    27.8 2880.99    50.3 2869.56    63.6 2864.99
    71.1 2863.04    77.1 2861.98    86.5 2860.61    98.9 2859.72   105.8 2858.46
   108.7 2857.66     117  2854.3   123.6 2853.53   127.5 2852.62   138.7 2847.73
   149.4  2845.2   157.7 2841.94   161.9 2841.16     166 2840.46   170.2 2840.54
  172.812841.146   178.6 2842.44   199.4 2845.92   201.1 2846.83     214 2855.45
   228.4 2866.37   242.2 2876.08   252.9 2884.07   269.3 2893.41     275 2896.99
#Mann= 3 ,-1,0
       0      .1       0   161.9    .045       0  172.81      .1       0
Bank Sta=161.9,172.81
XS Rating Curve= 0 ,0
Exp/Cntr(USF)=0,0
Exp/Cntr=0.3,0.1

Type RM Length L Ch R = 1 ,1194    ,121.7,118.9,114.9
XS GIS Cut Line= 6
2323127.00929103663829.4871787532323097.72712979 663822.69711238
2323074.81065578663771.3472354352323068.44496856663754.796448651
 2322982.7203806663701.3246759652322938.16057003663699.202780223
#Sta/Elev= 30
       0 2867.81     2.9 2865.93    15.2 2859.62    27.5 2853.72    33.9 2852.13
    40.5 2851.04    50.6 2850.36    79.9 2846.21    97.2 2846.09   101.5 2845.66
   104.3  2844.8     117 2836.64   121.52834.383   123.2  2833.8   127.9 2833.48
   134.4 2834.38   142.1 2835.64   160.9 2833.29   175.1 2833.31   182.7 2834.58
   186.7 2836.01   189.2 2837.53   193.9 2841.23   195.4 2842.03   198.3 2842.89
   205.1  2843.6   215.3 2847.33   223.6 2851.66   227.6 2854.25   249.7 2870.72
#Mann= 3 ,-1,0
       0      .1       0   121.5    .045       0   134.4      .1       0
Bank Sta=121.5,134.4
XS Rating Curve= 0 ,0
Exp/Cntr(USF)=0,0
Exp/Cntr=0.3,0.1

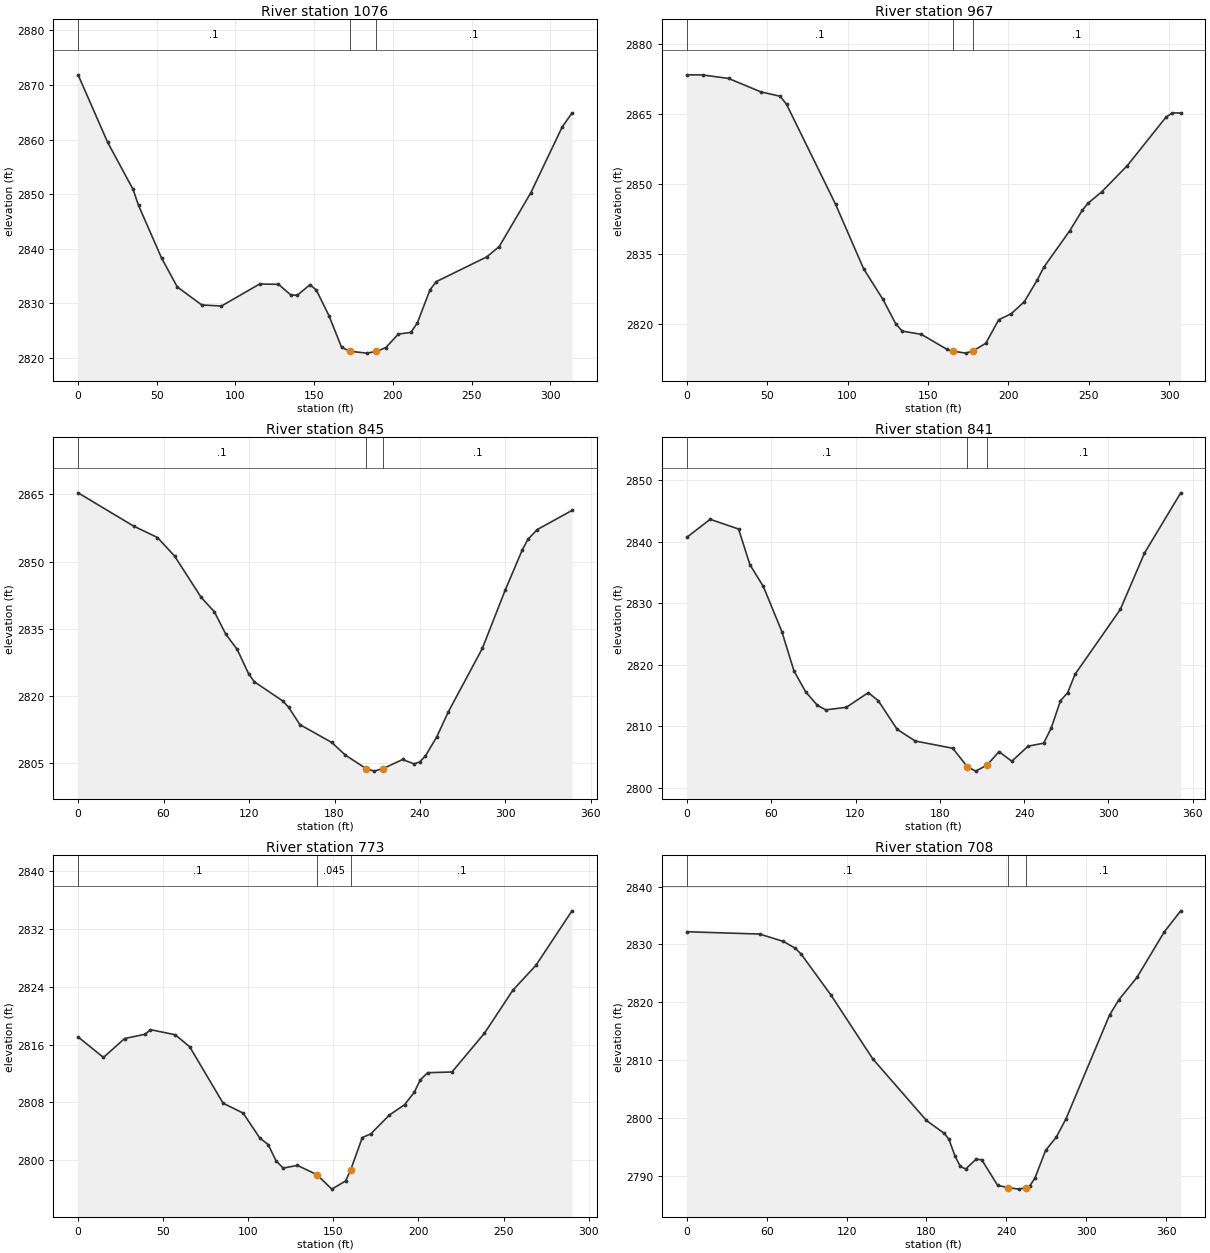
Type RM Length L Ch R = 1 ,1076    ,107.7,108.5,107
XS GIS Cut Line= 4
2323254.84736638 663621.710077562323123.48389167663635.082746081
 2323007.4405259663626.9954450632322942.07993407 663629.34890223
#Sta/Elev= 30
       0 2871.86    18.8 2859.46    34.9 2850.87    38.4 2847.91      53 2838.29
      63 2832.97    78.6 2829.66    91.1 2829.47   115.3  2833.5   127.3 2833.45
   135.4 2831.44   139.4 2831.48   147.4 2833.39   151.4 2832.37   159.4 2827.69
   167.4 2821.91172.86852821.161   183.5 2820.83   189.4 2821.14   195.5 2821.84
   203.5 2824.33   211.5 2824.63   215.6 2826.41   223.6 2832.44   227.6 2833.94
   259.6 2838.47   267.6 2840.38   287.7 2850.26   307.6 2862.31   313.8 2864.84
#Mann= 3 ,-1,0
       0      .1       0172.8685    .045       0   189.4      .1       0
Bank Sta=172.8685,189.4
XS Rating Curve= 0 ,0
Exp/Cntr(USF)=0,0
Exp/Cntr=0.3,0.1

Type RM Length L Ch R = 1 ,967     ,120.6,122,119.5
XS GIS Cut Line= 2
2323266.20565167663526.480466862 2322958.9551483663530.299879197
#Sta/Elev= 30
       0 2873.29      10 2873.26      26 2872.51      46 2869.64      58 2868.71
      62 2866.99    92.5 2845.59     110 2831.74     122  2825.2     130 2819.95
     134  2818.4     146 2817.69     162 2814.46   165.4 2814.12   173.5 2813.68
     178 2814.13     186 2815.79     194 2820.81   201.9 2822.14     210 2824.71
   218.1 2829.38     222 2832.03   238.3 2839.92     246 2844.25   249.6 2845.78
   258.1 2848.22   274.1 2853.86   298.1 2864.21   302.1 2865.15   307.3 2865.11
#Mann= 3 ,-1,0
       0      .1       0   165.4    .045       0     178      .1       0
Bank Sta=165.4,178
XS Rating Curve= 0 ,0
Exp/Cntr(USF)=0,0
Exp/Cntr=0.3,0.1

Type RM Length L Ch R = 1 ,845     ,4.5,4.2,5.1
XS GIS Cut Line= 4
2323270.44944315663466.2186278022323253.89865637663414.868750857
2322989.08606783663423.3563338242322965.32083552663437.785224866
#Sta/Elev= 30
       0 2865.36    38.9 2857.94    55.7 2855.37    67.7 2851.24    86.4 2841.99
    95.7 2838.75   103.7 2833.75   111.7 2830.36   119.7 2824.91   123.7 2823.13
   143.7 2818.83   147.7 2817.47   155.7 2813.55   178.1 2809.55   187.7 2806.72
   202.2 2803.71   207.8 2803.15   214.1 2803.72   227.8 2805.75   235.8 2804.77
   239.8  2805.2   243.8 2806.53   251.8 2810.82   259.8 2816.34   283.8  2830.6
   299.8 2843.59   311.8 2852.59   315.8 2854.98   322.4 2857.16   346.7 2861.42
#Mann= 3 ,-1,0
       0      .1       0   202.2    .045       0   214.1      .1       0
Bank Sta=202.2,214.1
XS Rating Curve= 0 ,0
Exp/Cntr(USF)=0,0
Exp/Cntr=0.3,0.1

Type RM Length L Ch R = 1 ,841     ,66.6,67.3,68.6
XS GIS Cut Line= 6
2323252.94346578663286.8170004312323194.80352247663336.044981635
2323165.52136123 663379.756033912323108.65455536 663414.97950322
2323076.82611924663410.7357117372322982.18956916663336.469360783
#Sta/Elev= 30
       0 2840.75    16.6 2843.67    36.8 2842.09    44.9 2836.27    54.4 2832.75
    67.6  2825.4    76.2 2819.01    84.6 2815.57    92.9  2813.4    98.8 2812.66
   113.4 2813.07   129.1 2815.46   136.2 2814.15   149.6  2809.5   162.4  2807.6
   189.2 2806.41   199.5 2803.42   205.5 2802.69   213.6 2803.67   222.1 2805.86
   231.2  2804.3   242.8 2806.75   253.9 2807.24   259.3 2809.73   265.8 2814.13
     271 2815.48   276.2 2818.45   308.4    2829   325.6 2838.17   351.4 2847.98
#Mann= 3 ,-1,0
       0      .1       0   199.5    .045       0   213.6      .1       0
Bank Sta=199.5,213.6
XS Rating Curve= 0 ,0
Exp/Cntr(USF)=0,0
Exp/Cntr=0.3,0.1

Type RM Length L Ch R = 1 ,773     ,65.3,65.5,62.6
XS GIS Cut Line= 6
2323206.68958358663261.0436705842323167.75448425663314.301768671
2323110.88767838663349.5252379812323079.05924226663345.281446498
2323025.16309042663292.6584321082322979.11727782663281.625924274
#Sta/Elev= 30
       0 2817.05    14.9 2814.22    27.3 2816.83    39.5 2817.43    42.5 2818.06
    57.1 2817.35    65.6 2815.68    85.2  2807.9      97 2806.52   106.8 2803.07
   111.7 2802.18   116.3 2799.94   120.5 2798.93   128.9  2799.3   140.3 2798.02
   149.1 2796.02   157.2 2797.15   160.1 2798.64     167 2803.15     172 2803.66
   182.9 2806.26   191.8 2807.68   197.5  2809.4   201.1 2811.12   205.4 2812.11
   219.7 2812.21   238.7 2817.54   255.5 2823.52     269 2826.94   290.2 2834.48
#Mann= 3 ,-1,0
       0      .1       0   140.3    .045       0   160.1      .1       0
Bank Sta=140.3,160.1
XS Rating Curve= 0 ,0
Exp/Cntr(USF)=0,0
Exp/Cntr=0.3,0.1

Type RM Length L Ch R = 1 ,708     ,99.6,100.6,96.2
XS GIS Cut Line= 4
 2323320.9505618663197.5866269242323148.22824844663284.584352327
2323027.28019117 663286.281868922322972.11090189663273.550494471
#Sta/Elev= 30
       0  2832.2    54.6  2831.8    72.5 2830.53    81.5 2829.34      86  2828.3
   108.4 2821.22   139.7 2810.24     180 2799.61   193.4 2797.38   196.9 2796.35
   201.4  2793.5   205.4 2791.69   209.4 2791.23   217.2 2792.91   221.5 2792.84
   233.5  2788.4   241.5 2788.03   241.5 2788.02   249.3 2787.76   255.1 2788.01
   257.5 2788.28   261.5 2789.68   269.5 2794.45   277.5 2796.73   284.8 2799.89
   317.5  2817.8   324.5 2820.45   338.1 2824.31   358.6 2832.16     371 2835.81
#Mann= 3 ,-1,0
       0      .1       0   241.5    .045       0   255.1      .1       0
Bank Sta=241.5,255.1
XS Rating Curve= 0 ,0
Exp/Cntr(USF)=0,0
Exp/Cntr=0.3,0.1

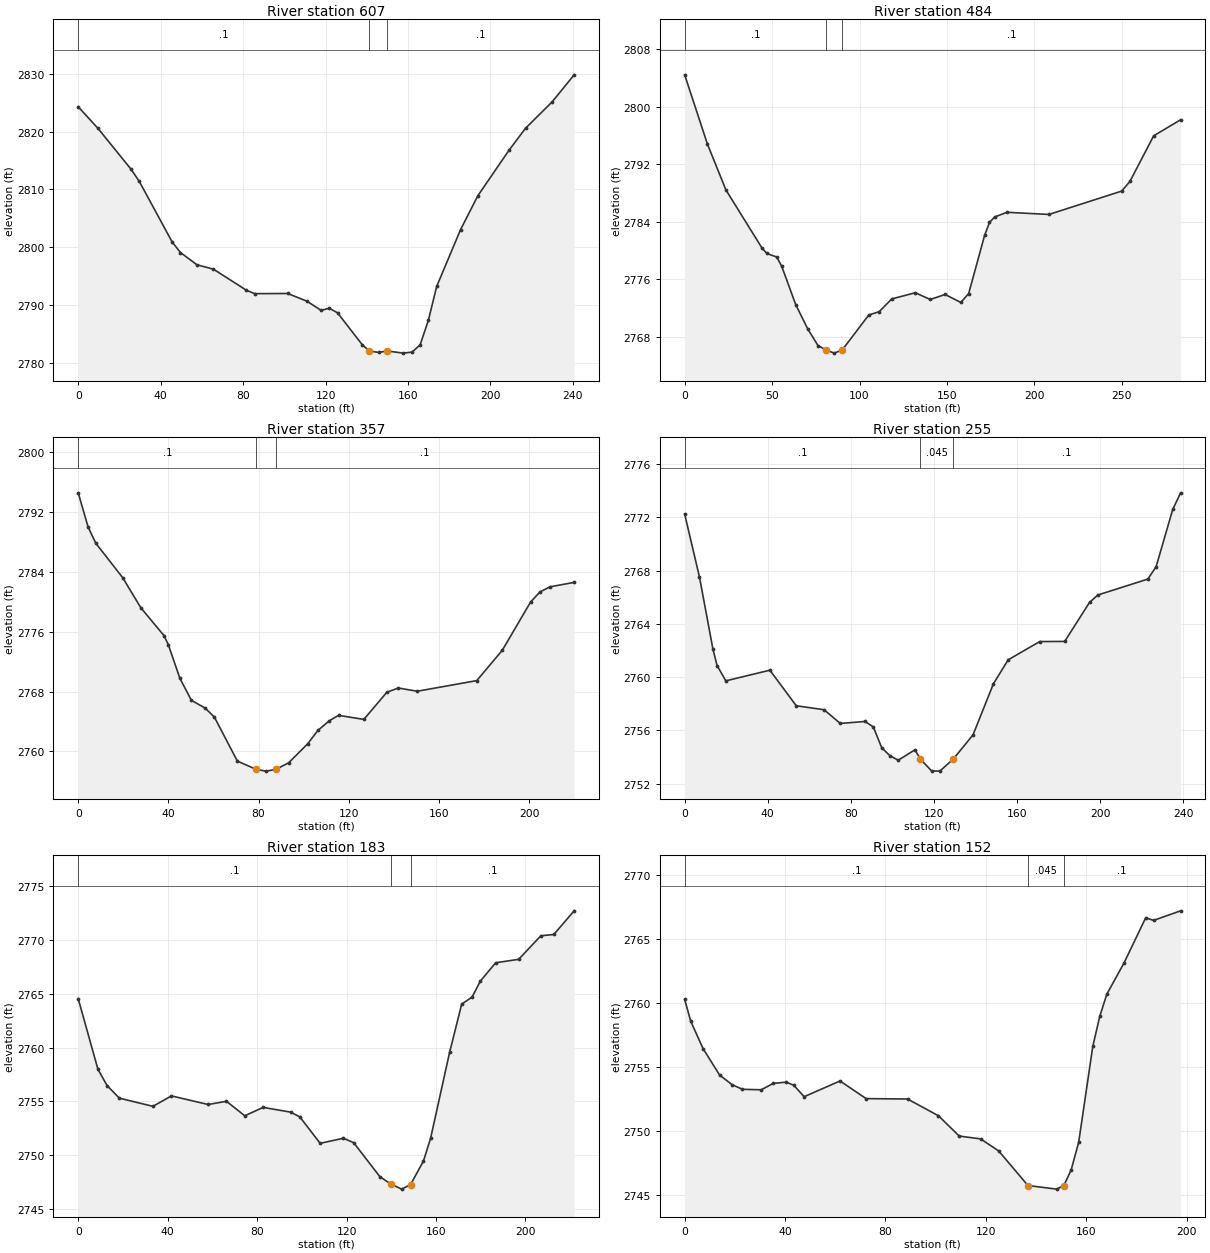
Type RM Length L Ch R = 1 ,607     ,119.1,123,125.6
XS GIS Cut Line= 5
2323229.69425859663197.6640513782323122.24371286663202.875067803
2323105.96316453663200.3371620522323030.09592389663201.801662379
2322989.45322274 663202.24734618
#Sta/Elev= 30
       0  2824.3     9.5  2820.6    25.5 2813.55    29.6 2811.41    45.6 2800.89
    49.6 2799.08    57.6 2796.96    65.6  2796.2    81.6 2792.55    85.6 2791.96
   101.6 2791.99   110.9 2790.67   117.8 2789.08   121.8 2789.43   125.8 2788.65
   137.8 2783.12   141.3 2782.03   145.8 2781.79149.93662782.042   157.7 2781.67
     162 2781.85   165.9 2783.12   169.9 2787.38   173.9  2793.2   185.5 2803.05
   193.9 2808.92   209.1 2816.83     217 2820.58   229.9 2825.14   240.6 2829.83
#Mann= 3 ,-1,0
       0      .1       0   141.3    .045       0149.9366      .1       0
Bank Sta=141.3,149.9366
XS Rating Curve= 0 ,0
Exp/Cntr(USF)=0,0
Exp/Cntr=0.3,0.1

Type RM Length L Ch R = 1 ,484     ,125.3,126.9,126.8
XS GIS Cut Line= 3
2323214.41660925663161.3796341982323052.09158503663008.603140807
2322998.61981234663037.248733318
#Sta/Elev= 30
       0 2804.44      13 2794.81    23.6 2788.42    44.2 2780.35      47 2779.59
    52.7 2779.09    55.5  2777.8    63.5 2772.48    70.3 2769.13    76.2 2766.79
      81 2766.16    85.5 2765.73    90.12766.173   105.3 2771.04   111.2 2771.49
   118.4 2773.27   131.9 2774.13   140.4 2773.19   148.9 2773.89   157.9 2772.78
   162.4 2774.01   171.5  2782.1   174.3  2783.9   177.2 2784.66   184.3 2785.32
   208.3 2785.02   249.9 2788.27   254.6 2789.61   268.2 2795.96   283.6 2798.19
#Mann= 3 ,-1,0
       0      .1       0      81    .045       0    90.1      .1       0
Bank Sta=81,90.1
XS Rating Curve= 0 ,0
Exp/Cntr(USF)=0,0
Exp/Cntr=0.3,0.1

Type RM Length L Ch R = 1 ,357     ,105.6,103,92.7
XS GIS Cut Line= 3
2323295.77009198663084.6094462692323202.57643102662966.589605125
2323133.06312652662970.027076226
#Sta/Elev= 30
       0 2794.54     4.4 2789.96     7.8 2787.81    19.7 2783.22    27.8 2779.18
    38.1 2775.45      40 2774.23    45.1 2769.77    50.2 2766.83    56.3 2765.79
    60.4 2764.59    70.6 2758.71      79  2757.6    83.3 2757.37    87.6 2757.59
    93.3 2758.47   101.8 2761.02   106.3  2762.8   111.4  2764.1   115.5 2764.82
   126.7 2764.28   136.9  2767.9     142 2768.47   150.4 2768.04   176.8 2769.46
   188.1  2773.5   200.7 2779.97   204.8 2781.29   209.2 2781.98     220 2782.58
#Mann= 3 ,-1,0
       0      .1       0      79    .045       0    87.6      .1       0
Bank Sta=79,87.6
XS Rating Curve= 0 ,0
Exp/Cntr(USF)=0,0
Exp/Cntr=0.3,0.1

Type RM Length L Ch R = 1 ,255     ,68.7,71.4,76.3
XS GIS Cut Line= 4
2323354.74654031663027.9357081792323327.44555379662948.971496539
2323255.28432124662946.7286609842323172.40307357662949.020308385
#Sta/Elev= 30
       0 2772.24     7.1 2767.53    13.6  2762.1    15.6 2760.87    19.8 2759.72
      41 2760.52    53.7 2757.85    67.1 2757.55    74.9 2756.52    86.8 2756.67
    90.8 2756.26    94.8 2754.71    98.8 2754.09   102.8 2753.76   110.8 2754.54
113.47642753.845   118.8 2752.96   122.8 2752.94129.27642753.845   138.8 2755.67
   148.6  2759.5   155.7  2761.3   170.9 2762.67   182.9 2762.68   194.9 2765.62
   198.9 2766.17   222.9 2767.36   226.9 2768.29   234.9 2772.59   238.7 2773.84
#Mann= 3 ,-1,0
       0      .1       0113.4764    .045       0129.2764      .1       0
Bank Sta=113.4764,129.2764
XS Rating Curve= 0 ,0
Exp/Cntr(USF)=0,0
Exp/Cntr=0.3,0.1

Type RM Length L Ch R = 1 ,183     ,29.2,31.3,32.1
XS GIS Cut Line= 4
2323368.26184916663009.7925203712323345.88542923662911.600211334
2323291.59067557662866.1900537342323246.92090098662889.388721204
#Sta/Elev= 30
       0 2764.56     8.8 2758.01    12.9 2756.48    18.4 2755.31    33.4 2754.55
    41.7 2755.52    58.1 2754.72    66.3 2755.02    74.5 2753.67    82.7 2754.45
      95 2754.01    99.1 2753.57   108.2 2751.11   118.6 2751.58   123.2 2751.17
   134.9 2748.01140.04642747.293   144.7 2746.85148.64642747.274   154.4 2749.46
   157.6 2751.58   166.1 2759.57   171.5 2764.05   176.2 2764.72   179.8 2766.18
   186.7  2767.9     197 2768.22   206.9 2770.41   212.7 2770.53   221.8 2772.73
#Mann= 3 ,-1,0
       0      .1       0140.0464    .045       0148.6464      .1       0
Bank Sta=140.0464,148.6464
XS Rating Curve= 0 ,0
Exp/Cntr(USF)=0,0
Exp/Cntr=0.3,0.1

Type RM Length L Ch R = 1 ,152     ,71.3,76.7,78.6
XS GIS Cut Line= 5
2323378.64780475662999.5024701032323351.53351207662886.763887328
2323324.61152446662848.4032733592323319.45044846662842.458704245
2323296.15203322662855.826647417
#Sta/Elev= 30
       0 2760.28     2.4 2758.58     7.3 2756.44    13.9 2754.37    18.8 2753.62
      23 2753.25    30.5 2753.21    35.3 2753.71    40.5 2753.81    43.5 2753.56
    47.6 2752.67    61.9  2753.9    72.3 2752.52    88.8 2752.49   101.1 2751.18
   109.4 2749.59   117.9 2749.37   125.1 2748.43136.77082745.723   148.2 2745.44
151.07082745.715     154 2746.95     157 2749.12   162.6  2756.6   165.4 2758.97
   168.2 2760.69   175.1 2763.15   183.7 2766.67   186.8 2766.46   197.6 2767.21
#Mann= 3 ,-1,0
       0      .1       0136.7708    .045       0151.0708      .1       0
Bank Sta=136.7708,151.0708
XS Rating Curve= 0 ,0
Exp/Cntr(USF)=0,0
Exp/Cntr=0.3,0.1

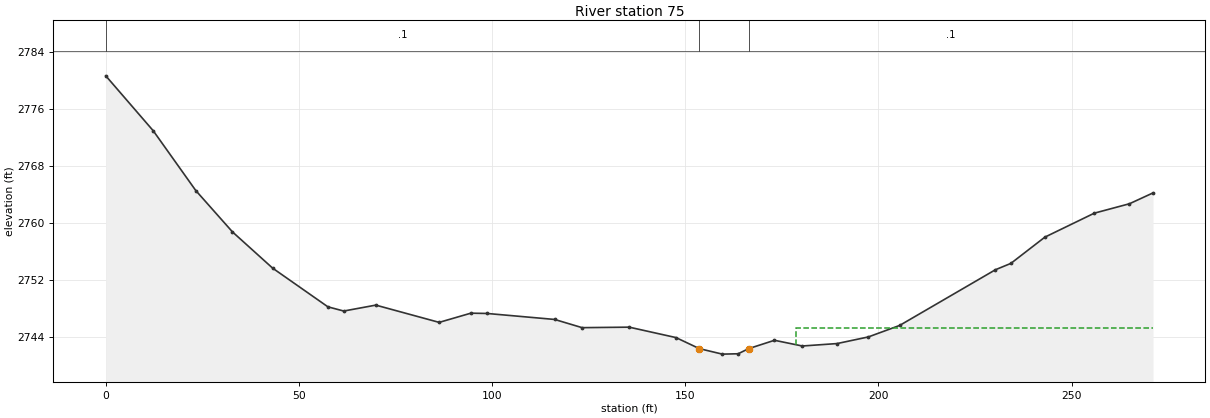
Type RM Length L Ch R = 1 ,75      ,,,
XS GIS Cut Line= 5
2323440.33462047663001.1231127852323410.29458116662875.640800959
2323405.98117504662833.5960213462323356.88672659662826.246776189
2323309.26726454662841.945385178
#Sta/Elev= 30
       0 2780.64    12.3 2772.93    23.3 2764.56    32.8 2758.76    43.2 2753.68
    57.5 2748.26    61.6 2747.67    69.9  2748.5    86.3 2746.08    94.5 2747.37
    98.7 2747.33   116.2 2746.49   123.3 2745.34   135.5 2745.41   147.6 2743.95
  153.672742.397   159.6 2741.63   163.7 2741.68  166.422742.401   173.1 2743.57
   180.3 2742.77   189.3 2743.11   197.4 2744.04   205.5 2745.65   230.3 2753.46
   234.3 2754.35   243.1 2758.03   255.9 2761.39     265 2762.71   271.1 2764.23
#Mann= 3 ,-1,0
       0      .1       0  153.67    .045       0  166.42      .1       0
#XS Ineff= 2 , 0
                          178.72         2745.25
Permanent Ineff=
       F       F
Bank Sta=153.67,166.42
XS Rating Curve= 0 ,0
Exp/Cntr(USF)=0,0
Exp/Cntr=0.3,0.1
LCMann Table=0

Chan Stop Cuts=-1
Use User Specified Reach Order=0
Composite Channel Slope=5